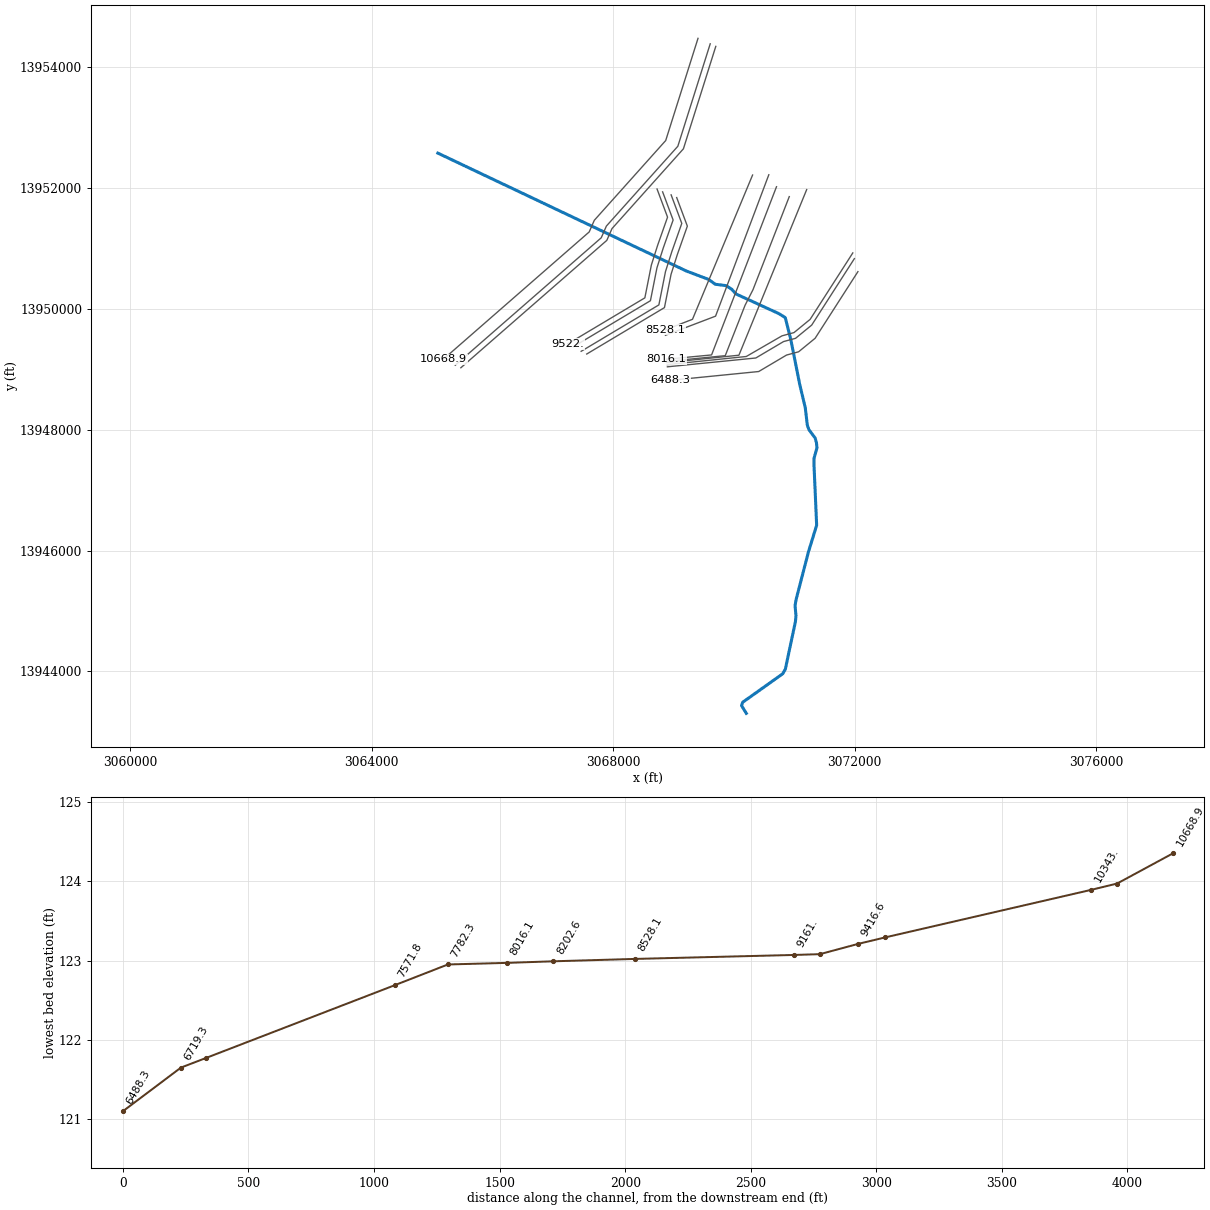
--- K131-04-00.prj (project) ---

Proj Title=K131-04-00
Current Plan=p05
Default Exp/Contr=.3,.1
English Units
Geom File=g01
Flow File=f07
Flow File=f04
Flow File=f05
Plan File=p07
Plan File=p04
Plan File=p05
Y Axis Title=Elevation
X Axis Title(PF)=Main Channel Distance
X Axis Title(XS)=Station
BEGIN DESCRIPTION:
Cypress Creek Watershed
Tributary to Spring Gully
HCFCD Unit K131-04-00
Flood Hazard Model
10, 2, 1, 0.2%
Filename K131-04-00
Prepared by:  Halff Associates DATE:  03-26-04
Reviewed by:  _____________________  DATE:  __________________
STATUS (Final)
END DESCRIPTION:
DSS Export Rating Curves= 0
DSS Export Rating Curve Sorted= 0
DSS Export Volume Flow Curves= 0
DXF OffsetX= 0
DXF OffsetY= 0
DXF ScaleX= 1
DXF ScaleY= 10

--- K131-04-00.p05 (plan) ---

Plan Title=Floodway
Version=Version 3.0.1  Mar 2001
Short Identifier=Floodway0607
Geom File=g01
Flow File=f05
Subcritical Flow
K Sum by GR= 0
Std Step Tol= 0.01
Critical Tol= 0.01
Num of Std Step Trials= 20
Max Error Tol= 0.3
Flow Tol Ratio= 0.001
Split Flow NTrial= 30
Split Flow Tol= 0.02
Split Flow Ratio= 0.02
Log Output Level= 0
Friction Slope Method= 1
Unsteady Friction Slope Method= 2
Parabolic Critical Depth
Global Vel Dist= 0 , 0 , 0
Global Log Level= 0
CheckData=True
Encroach Param=-1 ,0,0, 3
Encroach River=K131-04-00
Encroach Reach=Reach - 1
Encroach Node=10668.9
       1 4928.55 5065.85       1 4928.55 5065.85
Encroach Node=10557.9
       1    4350  5242.6       1    4350  5242.6
Encroach Node=10446.9
       1 4928.55 5065.85       1 4928.55 5065.85
Encroach Node=10343.
       1 4928.55 5083.47       1 4928.55 5083.47
Encroach Node=9522.
       1 4928.55    5085       1 4928.55    5085
Encroach Node=9416.6
       1 4928.55    5085       1 4928.55    5085
Encroach Node=9340.1
       1    4500  5242.6       1    4500  5242.6
Encroach Node=9263.6
       1 4928.55    5085       1 4928.55    5085
Encroach Node=9161.
       1 4928.55    5085       1 4928.55    5085
Encroach Node=8528.1
       1 4879.13 5126.04       1 4879.13 5126.04
Encroach Node=8202.6
       1    4715 5122.04       1    4715 5122.04
Encroach Node=8016.1
       1 4767.91    5100       1 4767.91    5100
Encroach Node=7782.3
       1    4690    5178       1    4690    5178
Encroach Node=7571.8
       1    4690    5180       1    4690    5180
Encroach Node=6818.
       1 4949.57    5300       1 4949.57    5300
Encroach Node=6719.3
       1  4956.4    5317       1  4956.4    5317
Encroach Node=6603.8
       1  4956.4    5965       1  4956.4    5965
Encroach Node=6488.3
       1  4956.4 5198.91       1  4956.4 5198.91
Encroach Node=6290.0
       1  4949.3 5095.53       1  4949.3 5095.53
Encroach Node=6223.0
       1  4949.3    6000       1  4949.3    6000
Encroach Node=6156.0
       1  4949.3  5048.3       1  4949.3  5048.3
Encroach Node=6053.
       1  4942.9  5052.9       1  4942.9  5052.9
Encroach Node=5775.
       1  4929.4  5059.4       1  4929.4  5059.4
Encroach Node=5671.2
       1    4954  5041.7       1    4954  5041.7
Encroach Node=5613.7
       1  4949.3    5400       1  4949.3    5400
Encroach Node=5556.2
       1    4954  5041.7       1    4954  5041.7
Encroach Node=5460.
       1  4905.9  5075.4       1  4905.9  5075.4
Encroach Node=5141.3
       1  4884.8  5064.8       1  4884.8  5064.8
Encroach Node=5007.3
       1 4893.15  5090.2       1 4893.15  5090.2
Encroach Node=4790.1
       1 4815.37  5071.3       1 4815.37  5071.3
Encroach Node=4692.
       1 4815.37  5071.3       1 4815.37  5071.3
Encroach Node=4591.8
       1  4926.9  5041.6       1  4926.9  5041.6
Encroach Node=4575.8
       1  4926.9  5041.6       1  4956.9  5041.6
Encroach Node=4559.8
       1  4926.9  5041.6       1  4926.9  5041.6
Encroach Node=4534.9
       1  4926.9  5041.6       1  4926.9  5041.6
Encroach Node=4357.2
       1 4857.66  5050.6       1 4857.66  5050.6
Encroach Node=4260.2
       1 4891.91  5063.6       1 4891.91  5063.6
Encroach Node=4125.4
       1    4812  5047.7       1    4812  5047.7
Encroach Node=3989.3
       1 3493.55    3575       1 3493.55    3575
Encroach Node=3978.3
       1 3493.55    3575       1 3493.55    3575
Encroach Node=3967.3
       1 3493.55    3575       1 3493.55    3575
Encroach Node=3869.
       1  4940.9  5030.9       1  4940.9  5030.9
Encroach Node=3693.3
       1    4927  5041.2       1    4927  5041.2
Encroach Node=3449.3
       1  4851.7 5120.23       1  4851.7 5120.23
Encroach Node=3025.6
       1    4958 5252.08       1    4958 5252.08
Encroach Node=2916.
       1    4904    5187       1    4904    5187
Encroach Node=2802.1
       1    4850    5154       1    4850    5154
Encroach Node=2739.6
       1    4850    5154       1    4850    5154
Encroach Node=2677.1
       1    4850    5154       1    4850    5154
Encroach Node=2643.0
       1    4850    5154       1    4850    5154
Encroach Node=2547.1
       1    4590    4863       1    4590    4863
Encroach Node=2483.6
       1    4590    4863       1    4590    4863
Encroach Node=2420.1
       1 4658.43 4739.52       1 4658.43 4739.52
Encroach Node=2330.
       1  4940.9  5030.9       1  4940.9  5030.9
Encroach Node=1338.8
       1  4955.3  5044.9       1  4955.3  5044.9
Encroach Node=1233.
       1 4956.07 5045.16       1 4956.07 5045.16
Encroach Node=1134.0
       1  4956.8  5045.4       1  4956.8  5045.4
Encroach Node=1123.5
       1  4948.3  5052.7       1  4948.3  5052.7
Encroach Node=1113.0
       1  4948.3  5052.7       1  4948.3  5052.7
Encroach Node=1013
       1  4948.3  5052.7       1  4948.3  5052.7
Encroach Reach=K131-04-00_0010
Encroach Node=10668.9
       1 4928.55 5065.85       0       0       0
Encroach Node=10557.9
       1    4350  5242.6       0       0       0
Encroach Node=10446.9
       1 4928.55 5065.85       0       0       0
Encroach Node=10343.
       1 4928.55 5083.47       0       0       0
Encroach Node=9522.
       1 4928.55    5085       0       0       0
Encroach Node=9416.6
       1 4928.55    5085       0       0       0
Encroach Node=9340.1
       1    4500  5242.6       0       0       0
Encroach Node=9263.6
       1 4928.55    5085       0       0       0
Encroach Node=9161.
       1 4928.55    5085       0       0       0
Encroach Node=8528.1
       1 4879.13 5126.04       0       0       0
Encroach Node=8202.6
       1    4715 5122.04       0       0       0
Encroach Node=8016.1
       1 4767.91    5100       0       0       0
Encroach Node=7782.3
       1    4690    5178       0       0       0
Encroach Node=7571.8
       1    4690    5180       0       0       0
Encroach Node=6818.
       1 4949.57    5300       0       0       0
Encroach Node=6719.3
       1  4956.4    5317       0       0       0
Encroach Node=6603.8
       1  4956.4    5965       0       0       0
Encroach Node=6488.3
       1  4956.4 5198.91       0       0       0
Encroach Node=6290.0
       1  4949.3 5095.53       0       0       0
Encroach Node=6223.0
       1  4949.3    6000       0       0       0
Encroach Node=6156.0
       1  4949.3  5048.3       0       0       0
Encroach Node=6053.
       1  4942.9  5052.9       0       0       0
Encroach Node=5775.
       1  4929.4  5059.4       0       0       0
Encroach Node=5671.2
       1    4954  5041.7       0       0       0
Encroach Node=5613.7
       1  4949.3    5400       0       0       0
Encroach Node=5556.2
       1    4954  5041.7       0       0       0
Encroach Node=5460.
       1  4905.9  5075.4       0       0       0
Encroach Node=5141.3
       1  4884.8  5064.8       0       0       0
Encroach Node=5007.3
       1 4893.15  5090.2       0       0       0
Encroach Node=4790.1
       1 4815.37  5071.3       0       0       0
Encroach Node=4692.
       1 4815.37  5071.3       0       0       0
Encroach Node=4591.8
       1  4926.9  5041.6       0       0       0
Encroach Node=4575.8
       1  4926.9  5041.6       0       0       0
Encroach Node=4559.8
       1  4926.9  5041.6       0       0       0
Encroach Node=4534.9
       1  4926.9  5041.6       0       0       0
Encroach Node=4357.2
       1 4857.66  5050.6       0       0       0
Encroach Node=4260.2
       1 4891.91  5063.6       0       0       0
Encroach Node=4125.4
       1    4812  5047.7       0       0       0
Encroach Node=3989.3
       1 3493.55    3575       0       0       0
Encroach Node=3978.3
       1 3493.55    3575       0       0       0
Encroach Node=3967.3
       1 3493.55    3575       0       0       0
Encroach Node=3869.
       1  4940.9  5030.9       0       0       0
Encroach Node=3693.3
       1    4927  5041.2       0       0       0
Encroach Node=3449.3
       1  4851.7 5120.23       0       0       0
Encroach Node=3025.6
       1    4958 5252.08       0       0       0
Encroach Node=2916.
       1    4904    5187       0       0       0
Encroach Node=2802.1
       1    4850    5154       0       0       0
Encroach Node=2739.6
       1    4850    5154       0       0       0
Encroach Node=2677.1
       1    4850    5154       0       0       0
Encroach Node=2643.0
       1    4850    5154       0       0       0
Encroach Node=2547.1
       1    4590    4863       0       0       0
Encroach Node=2483.6
       1    4590    4863       0       0       0
Encroach Node=2420.1
       1 4658.43 4739.52       0       0       0
Encroach Node=2330.
       1  4940.9  5030.9       0       0       0
Encroach Node=1338.8
       1  4955.3  5044.9       0       0       0
Encroach Node=1233.
       1 4956.07 5045.16       0       0       0
Encroach Node=1134.0
       1  4956.8  5045.4       0       0       0
Encroach Node=1123.5
       1  4948.3  5052.7       0       0       0
Encroach Node=1113.0
       1  4948.3  5052.7       0       0       0
Encroach Node=1013
       1  4948.3  5052.7       0       0       0
Computation Interval=1HOUR
Output Interval=1HOUR
Run HTab= 0
Run UNet= 0
Run PostProcess= 0
UNET Theta= 1
UNET ZTol= 0.02
UNET ZSATol= 0.1
UNET MxIter= 20
UNET MaxInSteps= 20
UNET DtIC= 0
UNET DtMin= 0
UNET MaxCRTS= 20
UNET WFStab= 2
UNET SFStab= 1
UNET WFX= 1
UNET SFX= 1
UNET Convert EG Bridges=-1
UNET Use Existing IB Tables=-1
Instantaneous Interval=1HOUR
DSS File=dss
Write IC File= 0
IC Time=0
Write Velocity= 0
Write Detailed= 0

--- K131-04-00.p04 (plan) ---

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Plan Title=Storage Routing
Short Identifier=Store_Rout
Geom File=g01
Flow File=f04
Encroach Param=-1 ,0,0, 0

--- K131-04-00.p07 (plan) ---

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Plan Title=FEMA Effective June 2007
Short Identifier=FEMAeff0607
Geom File=g01
Flow File=f07
Encroach Param= 0 ,0,0, 2

--- K131-04-00.f05 (steady flow) ---

Flow Title=Floodway
Version=Version 3.0.1  Mar 2001
Number of Profiles= 2
Profile Names=1PCT_100yr, 1PCTFloodway_100yrFW
River Rch & RM=K131-04-00,K131-04-00_0010,10668.9
    1149    1149
River Rch & RM=K131-04-00,K131-04-00_0010,9416.6
    1187    1187
River Rch & RM=K131-04-00,K131-04-00_0010,8528.1
    1233    1233
River Rch & RM=K131-04-00,K131-04-00_0010,7571.8
    1272    1272
River Rch & RM=K131-04-00,K131-04-00_0010,6719.3
    1302    1302
River Rch & RM=K131-04-00,K131-04-00_0010,6290.0
    1341    1341
River Rch & RM=K131-04-00,K131-04-00_0010,5671.2
    1410    1410
River Rch & RM=K131-04-00,K131-04-00_0010,4591.8
    1456    1456
River Rch & RM=K131-04-00,K131-04-00_0010,3989.3
    1532    1532
River Rch & RM=K131-04-00,K131-04-00_0010,1338.8
    1609    1609
Boundary for River Rch & Prof#=K131-04-00,K131-04-00_0010, 1
Up Type= 0
Dn Type= 3
Dn Slope=.0012
Boundary for River Rch & Prof#=K131-04-00,K131-04-00_0010, 2
Up Type= 0
Dn Type= 3
Dn Slope=.0012
DSS Import GetInterval= 0
DSS Import GetPeak= 0
DSS Import FillOption= 0

--- K131-04-00.f04 (steady flow) ---

Flow Title=Storage Routing
Version=Version 3.0.1  Mar 2001
Number of Profiles= 7
Profile Names=0.25*10% flood, 0.50*10%flood, 10% flood, 2% flood, 1% flood, 0.2%flood, 1.25*0.2% flood
River Rch & RM=K131-04-00,K131-04-00_0010,10668.9
      93     185     370     620     730     875    1094
River Rch & RM=K131-04-00,K131-04-00_0010,9416.6
      95     190     380     640     750     900    1125
River Rch & RM=K131-04-00,K131-04-00_0010,8016.1
     130     260     520     830    1010    1240    1550
River Rch & RM=K131-04-00,K131-04-00_0010,6719.3
     141     283     565     920    1070    1310    1638
River Rch & RM=K131-04-00,K131-04-00_0010,6488.3
     153     305     610    1000    1110    1380    2070
River Rch & RM=K131-04-00,K131-04-00_0010,5671.2
     165     330     660    1100    1180    1460    1825
River Rch & RM=K131-04-00,K131-04-00_0010,4591.8
     208     415     830    1240    1390    1730    2163
River Rch & RM=K131-04-00,K131-04-00_0010,1338.8
     233     465     930    1320    1550    1870    2338
Boundary for River Rch & Prof#=K131-04-00,K131-04-00_0010, 1
Up Type= 0
Dn Type= 3
Dn Slope=.0012
Boundary for River Rch & Prof#=K131-04-00,K131-04-00_0010, 2
Up Type= 0
Dn Type= 3
Dn Slope=.0012
Boundary for River Rch & Prof#=K131-04-00,K131-04-00_0010, 3
Up Type= 0
Dn Type= 3
Dn Slope=.0012
Boundary for River Rch & Prof#=K131-04-00,K131-04-00_0010, 4
Up Type= 0
Dn Type= 3
Dn Slope=.0012
Boundary for River Rch & Prof#=K131-04-00,K131-04-00_0010, 5
Up Type= 0
Dn Type= 3
Dn Slope=.0012
Boundary for River Rch & Prof#=K131-04-00,K131-04-00_0010, 6
Up Type= 0
Dn Type= 3
Dn Slope=.0012
Boundary for River Rch & Prof#=K131-04-00,K131-04-00_0010, 7
Up Type= 0
Dn Type= 3
Dn Slope=.0012
DSS Import GetInterval= 0
DSS Import GetPeak= 0
DSS Import FillOption= 0

--- K131-04-00.f07 (steady flow) ---

Flow Title=FEMA Effective June 2007
Version=Version 3.0.1  Mar 2001
Number of Profiles= 4
Profile Names=10PCT_10yr, 2PCT_50yr, 1PCT_100yr, 0.2PCT_500yr
River Rch & RM=K131-04-00,K131-04-00_0010,10668.9
     591     996    1149    1607
River Rch & RM=K131-04-00,K131-04-00_0010,9416.6
     615    1026    1187    1699
River Rch & RM=K131-04-00,K131-04-00_0010,8528.1
     645    1057    1233    1806
River Rch & RM=K131-04-00,K131-04-00_0010,7571.8
     676    1088    1272    1913
River Rch & RM=K131-04-00,K131-04-00_0010,6719.3
     691    1111    1302    1990
River Rch & RM=K131-04-00,K131-04-00_0010,6290.0
     714    1141    1341    2028
River Rch & RM=K131-04-00,K131-04-00_0010,5671.2
     745    1195    1410    2097
River Rch & RM=K131-04-00,K131-04-00_0010,4591.8
     768    1226    1456    2143
River Rch & RM=K131-04-00,K131-04-00_0010,3989.3
     845    1264    1532    2296
River Rch & RM=K131-04-00,K131-04-00_0010,1338.8
     883    1302    1609    2372
Boundary for River Rch & Prof#=K131-04-00,K131-04-00_0010, 1
Up Type= 0
Dn Type= 3
Dn Slope=.0012
Boundary for River Rch & Prof#=K131-04-00,K131-04-00_0010, 2
Up Type= 0
Dn Type= 3
Dn Slope=.0012
Boundary for River Rch & Prof#=K131-04-00,K131-04-00_0010, 3
Up Type= 0
Dn Type= 3
Dn Slope=.0012
Boundary for River Rch & Prof#=K131-04-00,K131-04-00_0010, 4
Up Type= 0
Dn Type= 3
Dn Slope=.0012
DSS Import GetInterval= 0
DSS Import GetPeak= 0
DSS Import FillOption= 0

--- K131-04-00.g01 (geometry) ---

Geom Title=K131-04-00 June 2007
Version=Version 3.0.1  Mar 2001

River Reach=K131-04-00      ,K131-04-00_0010
Reach XY= 30
       3065098.3      13952573.1      3069212.28     13950623.56
        3069579.       13950485.        3069692.       13950404.
      3069871.25       13950381.      3069962.62     13950323.26
      3070034.45     13950243.94      3070740.21     13949920.77
      3070851.17     13949852.73       3070942.5       13949492.
      3071089.89      13948750.3       3071182.5       13948363.
      3071216.62     13948073.22        3071243.       13947999.
      3071346.75       13947859.      3071367.75       13947782.
      3071376.34     13947698.22       3071327.5       13947523.
        3071326.     13947438.67        3071371.       13946417.
      3071235.72     13945979.47      3071030.86     13945189.54
       3071013.5     13945089.71      3071028.75       13944919.
      3071019.57     13944824.09      3070852.91     13944038.49
       3070809.5     13943961.24       3070145.5       13943489.
      3070127.21     13943434.33       3070206.5       13943306.

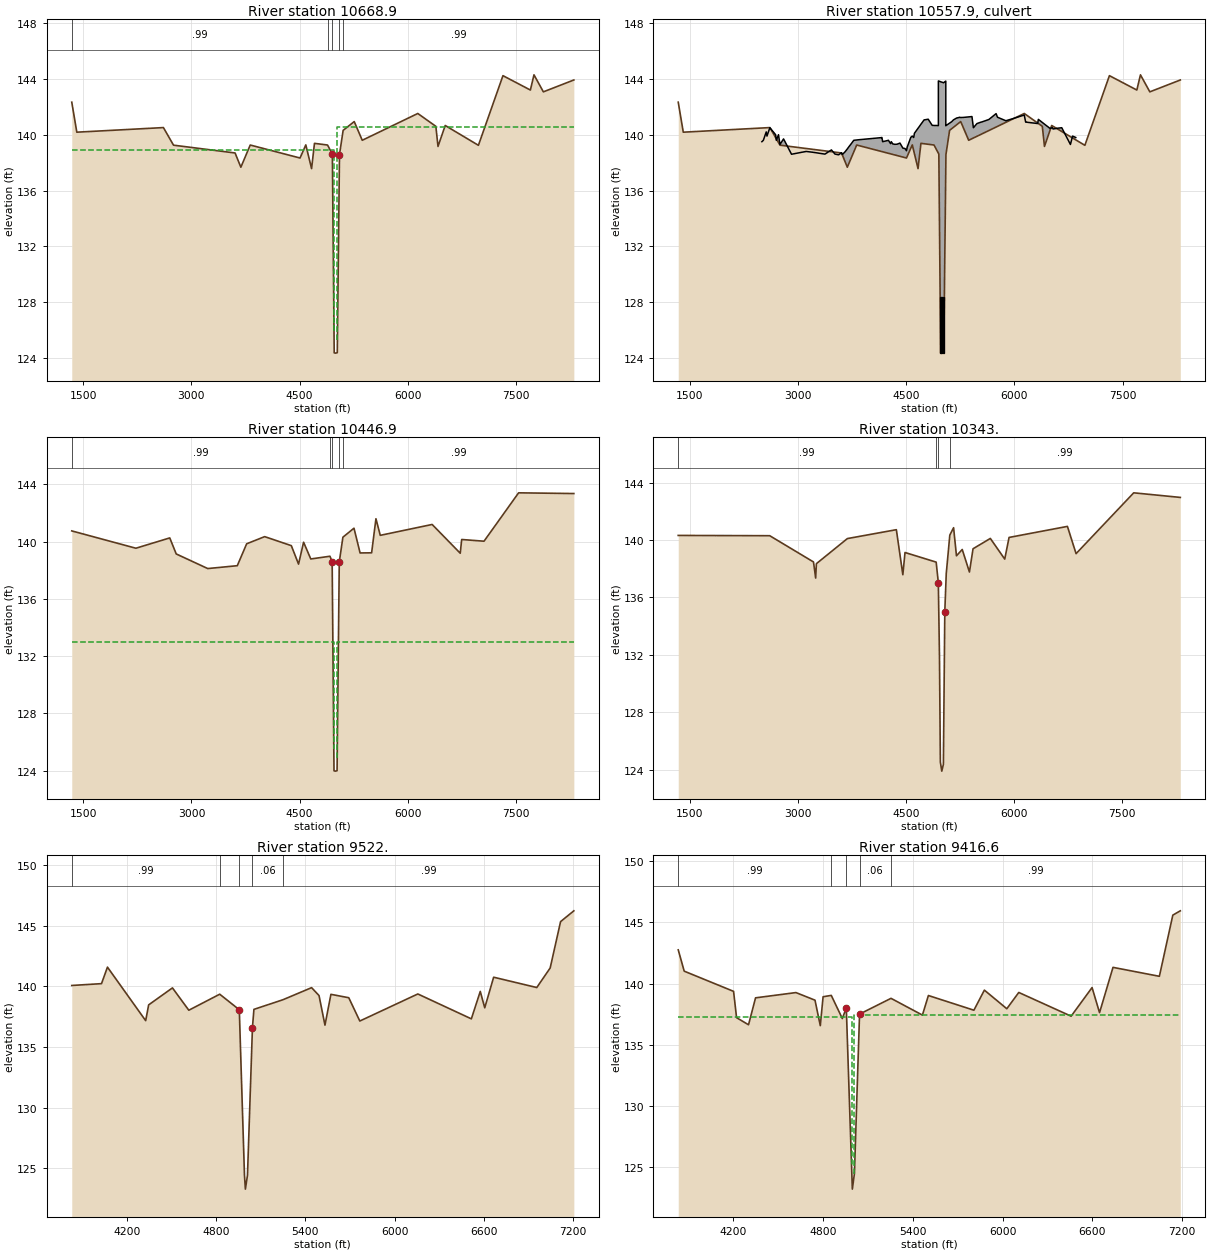
Type RM Length L Ch R = 1 ,10668.9 ,221,222,223
BEGIN DESCRIPTION:
Upstream Section of Bridge/Culvert/Weir
END DESCRIPTION:
XS GIS Cut Line= 5
      3069406.52     13954471.61      3068871.55     13952781.12
      3067689.47     13951462.08      3067604.61     13951269.21
      3065190.99     13949164.75
#Sta/Elev= 30
  1342.1  142.33  1412.1  140.18  2612.1  140.51  2752.1  139.25  3605.2  138.69
  3685.2  137.67  3815.2  139.26  4505.2  138.33  4585.2  139.27  4665.2  137.57
  4705.2  139.38  4886.4  139.26  4953.2  138.61  4978.8  124.37  4998.5  124.35
  5021.3  124.38  5051.9  138.58  5102.4  140.31  5256.2  140.94  5367.1   139.6
  6137.1  141.52  6387.1   140.6  6417.1  139.16  6517.1  140.66  6977.1  139.24
  7317.1  144.23  7697.1   143.2  7747.1  144.29  7877.1  143.07  8299.4  143.92
#Mann= 5 ,-1 , 0
  1342.1     .99       0  4886.4     .06       0  4953.2     .02       0
  5051.9     .06       0  5102.4     .99       0
#XS Ineff= 2 , 0
       0  4976.1  138.87  5023.2       0  140.52
Permanent Ineff=
       F       F
Bank Sta=4953.2,5051.9
XS Rating Curve= 0
Exp/Cntr=.5,.3

Type RM Length L Ch R = 2 ,10557.9 ,,,
BEGIN DESCRIPTION:
CULVERT 4000' US PINELAKES
Structure ID: K131-04-00-S10
END DESCRIPTION:
Bridge Culvert--1,0,-1,-1, 0
Deck Dist Width WeirC Skew NumUp NumDn MinLoCord MaxHiCord MaxSubmerge Is_Ogee
10,202,2.6,0, 125, 125, , , .95, 0, ,,,
  2501.6  2521.6  2561.6  2571.6  2611.6  2691.6  2701.6  2731.6  2751.6  2801.6
  2911.6  3114.7  3194.7  3274.7  3284.7  3361.5  3374.7  3384.7  3424.7  3434.7
  3464.7  3514.7  3534.7  3564.7  3604.7  3614.7  3654.7  3684.7  3694.7  3714.7
  3744.7  3774.7  3844.7  4154.7  4164.7  4174.6  4174.7  4224.7  4254.7  4284.7
  4294.7  4314.7  4344.7  4374.7  4414.7  4454.7  4484.6  4484.7  4504.7  4514.7
  4524.7  4564.7  4584.7  4604.7  4614.7  4664.7    4690  4693.8  4748.7  4805.9
  4861.2    4895  4922.3 4946.79  4946.9 4947.01    4949  4953.2  4966.4  4975.3
  4978.3  4978.8  4998.5  5017.6  5021.3  5021.7  5025.8  5038.1 5049.69  5049.8
 5049.91  5051.9  5076.8  5102.4  5130.8  5155.3  5184.3  5202.2    5205    5239
  5239.5  5256.2  5256.6  5296.6  5412.2  5432.2  5436.6  5476.6  5482.2  5536.6
  5546.6  5646.6  5746.6  5762.2  5766.6  5882.2  5972.2  6136.6  6156.6  6162.2
  6322.2  6332.2  6386.6  6396.6  6406.6  6426.6  6456.6  6496.6  6526.6  6536.6
  6607.2  6656.6  6776.6  6806.6  6850.8
   139.5   139.6   140.2   139.9   140.5     140   139.6     140   139.3   139.7
   138.6   138.8  138.75  138.69  138.68  138.62  138.61  138.64  138.78  138.81
  138.91  138.61  138.59  138.56  138.71  138.57  138.78  138.98  139.05  139.19
  139.39   139.6  139.64  139.79   139.8   139.5   139.5  139.56   139.6  139.36
   139.5  139.34  139.31  139.32   139.4  139.04  139.01  139.01  138.85  139.11
  139.25  139.81   139.9   139.8   140.1  140.46  140.64  140.67  141.06  141.11
  140.67  140.66  140.66  140.65  143.85  143.85  143.85  143.84  143.82   143.8
  143.79  143.79  143.76  143.72  143.73  143.74  143.75   143.8  143.84  143.84
  140.64  140.65  140.74  140.83  140.93  141.06  141.15   141.2   141.2  141.24
  141.25  141.23  141.23  141.24   141.3   140.5  140.53  140.77   140.8   140.9
  140.91  141.09  141.51   141.3  141.25     141  141.14  141.41   140.9   140.9
   140.8   141.1  140.88  140.84   140.8  140.72   140.6  140.44  140.51  140.41
  140.47   140.5   139.3   139.9   139.8
                                                                                
                                                                                
                                                                                
                                                                                
                                                                                
                                                                                
                                                                                
                                                                                
                                                                                
                                                                                
                                                                                
                                                                                
                                        
  2501.6  2521.6  2561.6  2571.6  2611.6  2691.6  2701.6  2731.6  2751.6  2801.6
  2911.6  3114.7  3194.7  3274.7  3284.7  3361.5  3374.7  3384.7  3424.7  3434.7
  3464.7  3514.7  3534.7  3564.7  3604.7  3614.7  3654.7  3684.7  3694.7  3714.7
  3744.7  3774.7  3844.7  4154.7  4164.7  4174.6  4174.7  4224.7  4254.7  4284.7
  4294.7  4314.7  4344.7  4374.7  4414.7  4454.7  4484.6  4484.7  4504.7  4514.7
  4524.7  4564.7  4584.7  4604.7  4614.7  4664.7    4690  4693.8  4748.7  4805.9
  4861.2    4895  4922.3 4946.79  4946.9 4947.01    4949  4953.2  4966.4  4975.3
  4978.3  4978.8  4998.5  5017.6  5021.3  5021.7  5025.8  5038.1 5049.69  5049.8
 5049.91  5051.9  5076.8  5102.4  5130.8  5155.3  5184.3  5202.2    5205    5239
  5239.5  5256.2  5256.6  5296.6  5412.2  5432.2  5436.6  5476.6  5482.2  5536.6
  5546.6  5646.6  5746.6  5762.2  5766.6  5882.2  5972.2  6136.6  6156.6  6162.2
  6322.2  6332.2  6386.6  6396.6  6406.6  6426.6  6456.6  6496.6  6526.6  6536.6
  6607.2  6656.6  6776.6  6806.6  6850.8
   139.5   139.6   140.2   139.9   140.5     140   139.6     140   139.3   139.7
   138.6   138.8  138.75  138.69  138.68  138.62  138.61  138.64  138.78  138.81
  138.91  138.61  138.59  138.56  138.71  138.57  138.78  138.98  139.05  139.19
  139.39   139.6  139.64  139.79   139.8   139.5   139.5  139.56   139.6  139.36
   139.5  139.34  139.31  139.32   139.4  139.04  139.01  139.01  138.85  139.11
  139.25  139.81   139.9   139.8   140.1  140.46  140.64  140.67  141.06  141.11
  140.67  140.66  140.66  140.65  143.85  143.85  143.85  143.84  143.82   143.8
  143.79  143.79  143.76  143.72  143.73  143.74  143.75   143.8  143.84  143.84
  140.64  140.65  140.74  140.83  140.93  141.06  141.15   141.2   141.2  141.24
  141.25  141.23  141.23  141.24   141.3   140.5  140.53  140.77   140.8   140.9
  140.91  141.09  141.51   141.3  141.25     141  141.14  141.41   140.9   140.9
   140.8   141.1  140.88  140.84   140.8  140.72   140.6  140.44  140.51  140.41
  140.47   140.5   139.3   139.9   139.8
                                                                                
                                                                                
                                                                                
                                                                                
                                                                                
                                                                                
                                                                                
                                                                                
                                                                                
                                                                                
                                                                                
                                                                                
                                        
BR Coef= 1 , 0 , 0 ,1.25, 0 ,,,.8,0,2,0,
WSPro=,,,, 1 ,,,, 0 ,,,, 0 ,,,,-1 ,-1 ,-1 , 0 , 0 , 0 , 0 , 0
Culvert=2,4,8,202,.015,.5,1,8,3,124.36,4980.1,123.99,4980.1,Culvert #1  , 0 ,10
Culvert Bottom n=.015
Culvert=2,4,8,202,.015,.5,1,8,3,124.36,4990.2,123.98,4990.2,Culvert #2  , 0 ,10
Culvert Bottom n=.015
Culvert=2,4,8,202,.015,.5,1,8,3,124.36,5000,123.99,5000,Culvert #3  , 0 ,10
Culvert Bottom n=.015
Culvert=2,4,8,202,.015,.5,1,8,3,124.36,5009.8,123.97,5009.8,Culvert #4  , 0 ,10
Culvert Bottom n=.015
Culvert=2,4,8,202,.015,.5,1,8,3,124.35,5019.2,123.98,5019.2,Culvert #5  , 0 ,10
Culvert Bottom n=.015
BR D #Sta/Elev= 91
  1339.2  140.75  1499.2  141.28  1539.2  140.51  2219.2  139.88  2229.2  139.54
  2279.2  139.75  2389.2  139.76  2419.2   139.5  2699.2  140.26  2719.2   139.8
  2749.2  139.96  2789.2  139.14  3116.6  138.72  3226.6  138.12  3336.6  138.52
  3466.6  138.44  3486.6  138.86  3616.6  138.74  3636.6  138.32  3766.6  139.85
  3986.6   139.9  3996.6  140.28  4016.6  140.35  4096.6  140.08  4326.6   139.8
  4336.6  139.25  4386.6  139.72  4456.6  138.48  4466.6  138.63  4486.6  138.43
  4526.6  139.23  4546.6  139.48  4556.6  139.96  4656.6  138.79  4686.6  139.29
  4696.6   138.9  4726.6  139.29  4786.6  138.99  4796.6  139.35  4816.6   139.2
  4826.6  139.55    4895  138.93  4922.3  138.98  4953.2  138.61  4966.4  131.69
  4975.3  126.41  4978.3  124.66  4978.8  123.99  4998.5  123.97  5021.3     124
  5021.7  124.62  5025.8  126.18  5038.1  132.42  5051.9  138.58  5102.4  140.31
  5155.3  141.05    5205  140.88  5256.2  140.94  5300.9   139.6  5340.9  139.21
  5360.9  139.78  5410.9  139.19  5450.9  139.71  5500.9  139.22  5520.9   139.7
  5560.9   141.6  5620.9  140.44  5810.9  140.37  6200.9  140.87  6340.9   141.2
  6670.9  139.93  6710.9  139.45  6720.9  139.63  6730.9  139.19  6750.9  140.15
  6830.9  140.28  6850.9   139.8  7060.9  140.03  7180.9   140.7  7190.9  141.19
  7200.9  141.03  7420.9  142.81  7430.9  142.19  7540.9  143.41  7560.9  143.01
  7610.9  143.36  7780.9  142.76  8040.9  143.17  8170.9  143.21  8200.9  142.96
  8307.6  143.36
BR D #Mann= 5
  1339.2     .99  4922.3     .06  4953.2     .02  5051.9     .06  5102.4     .99
BC Design=,, 0 ,, 0 ,,,,,,
BC HTab HWMax=144.27

Type RM Length L Ch R = 1 ,10446.9 ,101.6,103.9,105
BEGIN DESCRIPTION:
Downstream Section of Bridge/Culvert/Weir
END DESCRIPTION:
XS GIS Cut Line= 5
      3069608.68     13954381.11      3069072.41     13952686.51
      3067889.58     13951366.65       3067804.2      13951172.6
      3065387.22     13949065.21
#Sta/Elev= 30
  1339.2  140.75  2229.2  139.54  2699.2  140.26  2789.2  139.14  3226.6  138.12
  3636.6  138.32  3766.6  139.85  4016.6  140.35  4386.6  139.72  4486.6  138.43
  4556.6  139.96  4656.6  138.79  4922.3  138.98  4953.2  138.61  4978.8  123.99
  4998.5  123.97  5021.3     124  5051.9  138.58  5102.4  140.31  5256.2  140.94
  5340.9  139.21  5500.9  139.22  5560.9   141.6  5620.9  140.44  6340.9   141.2
  6730.9  139.19  6750.9  140.15  7060.9  140.03  7540.9  143.41  8307.6  143.36
#Mann= 5 ,-1 , 0
  1339.2     .99       0  4922.3     .06       0  4953.2     .04       0
  5051.9     .06       0  5102.4     .99       0
#XS Ineff= 2 , 0
       0  4976.1     133  5023.2       0     133
Permanent Ineff=
       F       F
Bank Sta=4953.2,5051.9
XS Rating Curve= 0
Exp/Cntr=.5,.3

Type RM Length L Ch R = 1 ,10343.  ,815.2,821,830.2
BEGIN DESCRIPTION:
K131-04-00-S10_CULVERT -DS - XS 1
END DESCRIPTION:
XS GIS Cut Line= 5
      3069700.92      13954338.5      3069164.65     13952643.94
      3067981.82     13951324.07      3067896.44     13951130.03
      3065479.46     13949022.64
#Sta/Elev= 30
  1340.7  140.32  2610.7   140.3  3218.1  138.47  3248.1  137.35  3258.1  138.35
  3688.1   140.1  4368.1  140.72  4458.1  137.58  4488.1  139.13  4920.5  138.46
  4950.5  137.03  4966.5  131.89 4978.76  124.53 4998.25  123.89 5020.82  124.36
  5040.5  135.01  5060.5  137.65    5110  140.34  5162.4  140.86  5202.4   138.9
  5282.4  139.34  5382.4  137.77  5432.4  139.39  5672.4  140.11  5872.4  138.67
  5932.4  140.18  6742.4  140.95  6862.4  139.05  7662.4  143.29  8309.1  142.97
#Mann= 4 ,-1 , 0
  1340.7     .99       0  4920.5     .06       0  4950.5     .04       0
    5110     .99       0
Bank Sta=4950.5,5040.5
XS Rating Curve= 0
Exp/Cntr=.3,.1

Type RM Length L Ch R = 1 ,9522.   ,107,105.4,102.9
BEGIN DESCRIPTION:
K131-04-00-S09_TC JESTER -US - XS 4
END DESCRIPTION:
XS GIS Cut Line= 6
      3068728.24      13951979.5      3068902.13       13951514.
      3068739.75     13951053.92      3068634.27     13950722.61
      3068526.29     13950178.93      3067247.32     13949416.04
#Sta/Elev= 30
  3828.8  140.07  4028.8  140.22  4068.8  141.58  4325.8  137.17  4345.8  138.47
  4505.8  139.87  4615.8  138.03  4823.7  139.35 4955.35  138.07 4990.08  124.44
 4996.26  123.29 5010.41  124.44  5043.7   136.6  5053.7   138.1    5250   138.9
  5441.4  139.89  5491.4  139.24  5531.4   136.8  5571.4  139.34  5691.4  139.06
  5765.7  137.14  6155.7  139.37  6515.7  137.32  6575.7  139.58  6605.7  138.23
  6665.7  140.75  6955.7   139.9  7045.7  141.51  7115.7  145.33  7204.9  146.22
#Mann= 5 ,-1 , 0
  3828.8     .99       0  4823.7     .06       0 4955.35     .04       0
  5043.7     .06       0    5250     .99       0
Bank Sta=4955.35,5043.7
XS Rating Curve= 0
Exp/Cntr=.5,.3

Type RM Length L Ch R = 1 ,9416.6  ,152,153,154.5
BEGIN DESCRIPTION:
Upstream Section of Bridge/Culvert/Weir
END DESCRIPTION:
XS GIS Cut Line= 6
      3068820.48     13951932.29      3068994.37     13951466.69
      3068831.99     13951006.62      3068726.51     13950675.31
      3068618.53     13950131.63      3067339.56     13949368.73
#Sta/Elev= 30
  3831.9  142.76  3871.9  141.02  4201.9  139.37  4221.9  137.22  4301.9  136.64
  4348.9  138.84  4618.9  139.27  4746.3  138.65  4781.7  136.57  4800.4  138.93
  4855.1  139.04    4929  137.15  4955.6  138.01    4996  123.21    5010  124.49
  5044.2  137.51  5254.5   138.8  5464.5  137.43  5504.5  139.03  5808.8  137.83
  5878.8  139.47  6028.8  137.95  6108.8  139.28  6458.8  137.34  6598.8  139.68
  6648.8  137.63  6738.8  141.33  7048.8   140.6  7138.8   145.6  7188.8  145.95
#Mann= 5 ,-1 , 0
  3831.9     .99       0  4855.1     .06       0  4955.6     .04       0
  5044.2     .06       0  5254.5     .99       0
#XS Ineff= 2 , 0
       0 4990.79  137.24  5009.2       0  137.46
Permanent Ineff=
       F       F
Bank Sta=4955.6,5044.2
XS Rating Curve= 0
Exp/Cntr=.5,.3

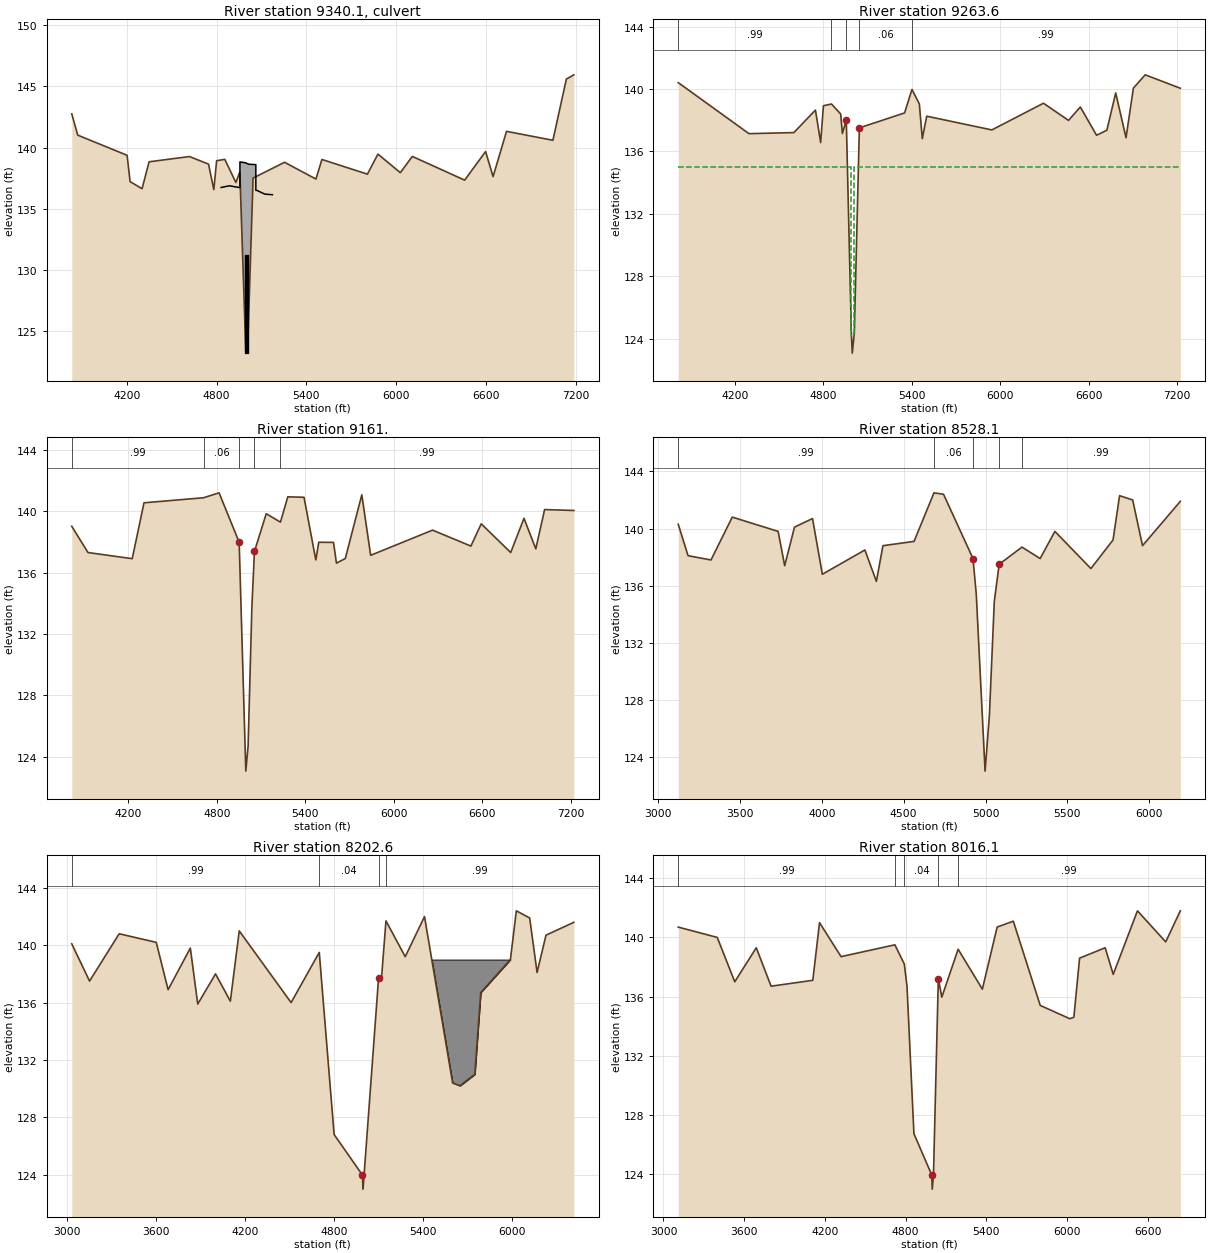
Type RM Length L Ch R = 2 ,9340.1  ,,,
BEGIN DESCRIPTION:
T.C.JESTER
Structure ID: K131-04-00-S09
END DESCRIPTION:
Bridge Culvert--1,0,-1,-1, 0
Deck Dist Width WeirC Skew NumUp NumDn MinLoCord MaxHiCord MaxSubmerge Is_Ogee
10,133,2.6,0, 13, 13, , , .95, 0, ,,,
  4830.8  4885.8    4941 4956.29  4956.3    4994  5007.3  5018.3  5062.6 5062.61
  5070.2  5122.2  5172.9
  136.74  136.88  136.76  136.73  138.83  138.76  138.68  138.64  138.61  136.51
   136.5   136.2  136.15
                                                                                
                        
  4830.8  4885.8    4941 4956.29  4956.3    4994  5007.3  5018.3  5062.6 5062.61
  5070.2  5122.2  5172.9
  136.74  136.88  136.76  136.73  138.83  138.76  138.68  138.64  138.61  136.51
   136.5   136.2  136.15
                                                                                
                        
BR Coef= 1 , 0 , 0 ,1.25, 0 ,,,.8,0,2,0,
WSPro=,,,, 1 ,,,, 0 ,,,, 0 ,,,,-1 ,-1 ,-1 , 0 , 0 , 0 , 0 , 0
Culvert=2,8,8,133,.015,.5,1,8,1,123.2,4994.8,123.16,4994.8,Culvert #1  , 0 ,10
Culvert Bottom n=.015
Culvert=2,8,8,133,.015,.5,1,8,1,123.21,5005.2,123.08,5005.2,Culvert #2  , 0 ,10
Culvert Bottom n=.015
BC Design=,, 0 ,, 0 ,,,,,,
BC HTab HWMax=139.71

Type RM Length L Ch R = 1 ,9263.6  ,104,102.6,102
BEGIN DESCRIPTION:
Downstream Section of Bridge/Culvert/Weir
END DESCRIPTION:
XS GIS Cut Line= 6
       3068961.3     13951882.72      3069137.73     13951410.32
      3068973.04     13950943.69        3068868.     13950613.74
       3068758.5     13950062.44      3067471.89     13949294.99
#Sta/Elev= 30
  3815.6  140.41  4295.6  137.14  4599.9  137.21  4746.3  138.65  4781.7  136.57
  4800.4  138.93  4855.1  139.04  4917.6   138.4    4929  137.15  4955.6  138.01
  4989.9  124.36    4996  123.08    5010  124.36  5044.2  137.51    5351  138.47
    5401  139.97    5451  139.05    5471  136.82    5501  138.26    5943  137.38
    6293  139.09    6463  137.99    6543  138.85    6653  137.04    6723  137.36
    6783  139.75    6853  136.88    6903  140.06    6983  140.91  7221.2  140.05
#Mann= 5 ,-1 , 0
  3815.6     .99       0  4855.1     .06       0  4955.6     .04       0
  5044.2     .06       0    5401     .99       0
#XS Ineff= 2 , 0
       0 4990.79     135  5009.2       0     135
Permanent Ineff=
       F       F
Bank Sta=4955.6,5044.2
XS Rating Curve= 0
Exp/Cntr=.5,.3

Type RM Length L Ch R = 1 ,9161.   ,634.8,632.9,622.5
BEGIN DESCRIPTION:
K131-04-00-S09_TC JESTER -DS - XS 1
END DESCRIPTION:
XS GIS Cut Line= 6
      3069053.54      13951837.7      3069229.97     13951365.38
      3069065.28     13950898.75      3068960.23     13950568.81
      3068850.74      13950017.5      3067564.13     13949250.05
#Sta/Elev= 30
  3815.7  139.02  3925.7  137.31  4225.7  136.91  4305.7  140.55    4710  140.88
  4814.8   141.2  4951.2  137.98  4996.2  123.07 5011.73  124.69 5037.35  133.75
  5054.8  137.38  5134.8  139.84  5231.1  139.29  5281.1  140.94  5391.1  140.91
  5471.1  136.83  5491.1  137.98  5591.1  137.97  5611.1  136.62  5671.1  136.92
  5783.1  141.07  5843.1  137.13  6263.1  138.77  6523.1  137.73  6593.1  139.18
  6793.1  137.31  6883.1  139.54  6963.1  137.55  7023.1  140.11  7221.3  140.05
#Mann= 5 ,-1 , 0
  3815.7     .99       0    4710     .06       0  4951.2     .04       0
  5054.8     .06       0  5231.1     .99       0
Bank Sta=4951.2,5054.8
XS Rating Curve= 0
Exp/Cntr=.3,.1

Type RM Length L Ch R = 1 ,8528.1  ,313.4,325.5,330
BEGIN DESCRIPTION:
Cross Section K131-04-00_Interpolated- XS15
END DESCRIPTION:
XS GIS Cut Line= 3
      3070310.12     13952210.39      3069315.17     13949824.39
       3068867.2     13949649.91
#Sta/Elev= 30
  3123.7   140.3  3183.7   138.1  3323.7   137.8  3453.7   140.8  3733.7   139.8
  3773.7   137.4  3833.7   140.1  3943.7   140.7  4003.7   136.8  4263.7   138.5
  4333.7   136.3  4373.7   138.8  4563.7   139.1  4685.4   142.5  4743.7   142.4
  4923.6   137.9  4943.7   135.4  4997.4  123.02  5023.7   126.9  5053.7   134.9
  5083.6   137.5  5222.8   138.7  5333.7   137.9  5423.7   139.8  5643.7   137.2
  5778.8   139.2  5818.8   142.3  5898.8     142  5958.8   138.8  6189.6   141.9
#Mann= 5 ,-1 , 0
  3123.7     .99       0  4685.4     .06       0  4923.6     .04       0
  5083.6     .06       0  5222.8     .99       0
Bank Sta=4923.6,5083.6
XS Rating Curve= 0
Exp/Cntr=.3,.1

Type RM Length L Ch R = 1 ,8202.6  ,188,186.5,173.3
BEGIN DESCRIPTION:
Cross Section K131-04-00_Interpolated- XS14; Detention pond on left VRR
END DESCRIPTION:
XS GIS Cut Line= 3
       3070578.9      13952215.1      3069697.11     13949876.26
       3068867.2     13949560.32
#Sta/Elev= 30
  3032.2   140.1  3152.2   137.5  3352.2   140.8  3602.2   140.2  3682.2   136.9
  3832.2   139.8  3882.2   135.9  4002.2     138  4102.2   136.1  4162.2     141
  4512.2     136  4702.1   139.5  4802.2   126.8  4993.6  123.97  4997.4  122.99
  5102.2   137.7  5122.2   137.7  5152.1   141.7  5282.2   139.2  5412.2     142
  5601.8   130.4  5651.8   130.2  5751.8     131  5791.8   136.7  5991.8     139
  6031.8   142.4  6121.8   141.9  6171.8   138.1  6231.8   140.7  6419.8   141.6
#Mann= 4 ,-1 , 0
  3032.2     .99       0  4702.1     .04       0  5102.2     .06       0
  5152.1     .99       0
#Block Obstruct= 1 ,-1
  5411.4  6023.9     139
Bank Sta=4993.6,5102.2
XS Rating Curve= 0
Exp/Cntr=.3,.1

Type RM Length L Ch R = 1 ,8016.1  ,241.5,233.8,227.1
BEGIN DESCRIPTION:
Cross Section K131-04-00_Interpolated- XS13; Two detention ponds on right VRR
END DESCRIPTION:
XS GIS Cut Line= 3
      3070706.21     13952017.06       3069631.1     13949234.96
      3068886.06     13949164.23
#Sta/Elev= 30
  3109.8   140.7  3399.8     140  3529.8     137  3689.8   139.3  3799.8   136.7
  4109.8   137.1  4159.8     141  4319.8   138.7  4719.8   139.5  4789.8   138.2
  4809.8   136.7  4861.3  126.72  4993.6  123.93  4997.4  122.97  5006.4   123.9
  5042.6   137.2  5068.6  135.96  5189.8   139.2  5369.8   136.5  5479.8   140.7
  5599.8   141.1  5799.8   135.4  6019.8   134.5  6049.8   134.6  6092.4   138.6
  6282.4   139.3  6342.4   137.5  6522.4   141.8  6732.4   139.7  6840.8   141.8
#Mann= 5 ,-1 , 0
  3109.8     .99       0  4719.8     .06       0  4789.8     .04       0
  5042.6     .06       0  5189.8     .99       0
#Block Obstruct= 2 , 0
       0                    5203       0     139
Bank Sta=4993.6,5042.6
XS Rating Curve= 0
Exp/Cntr=.3,.1

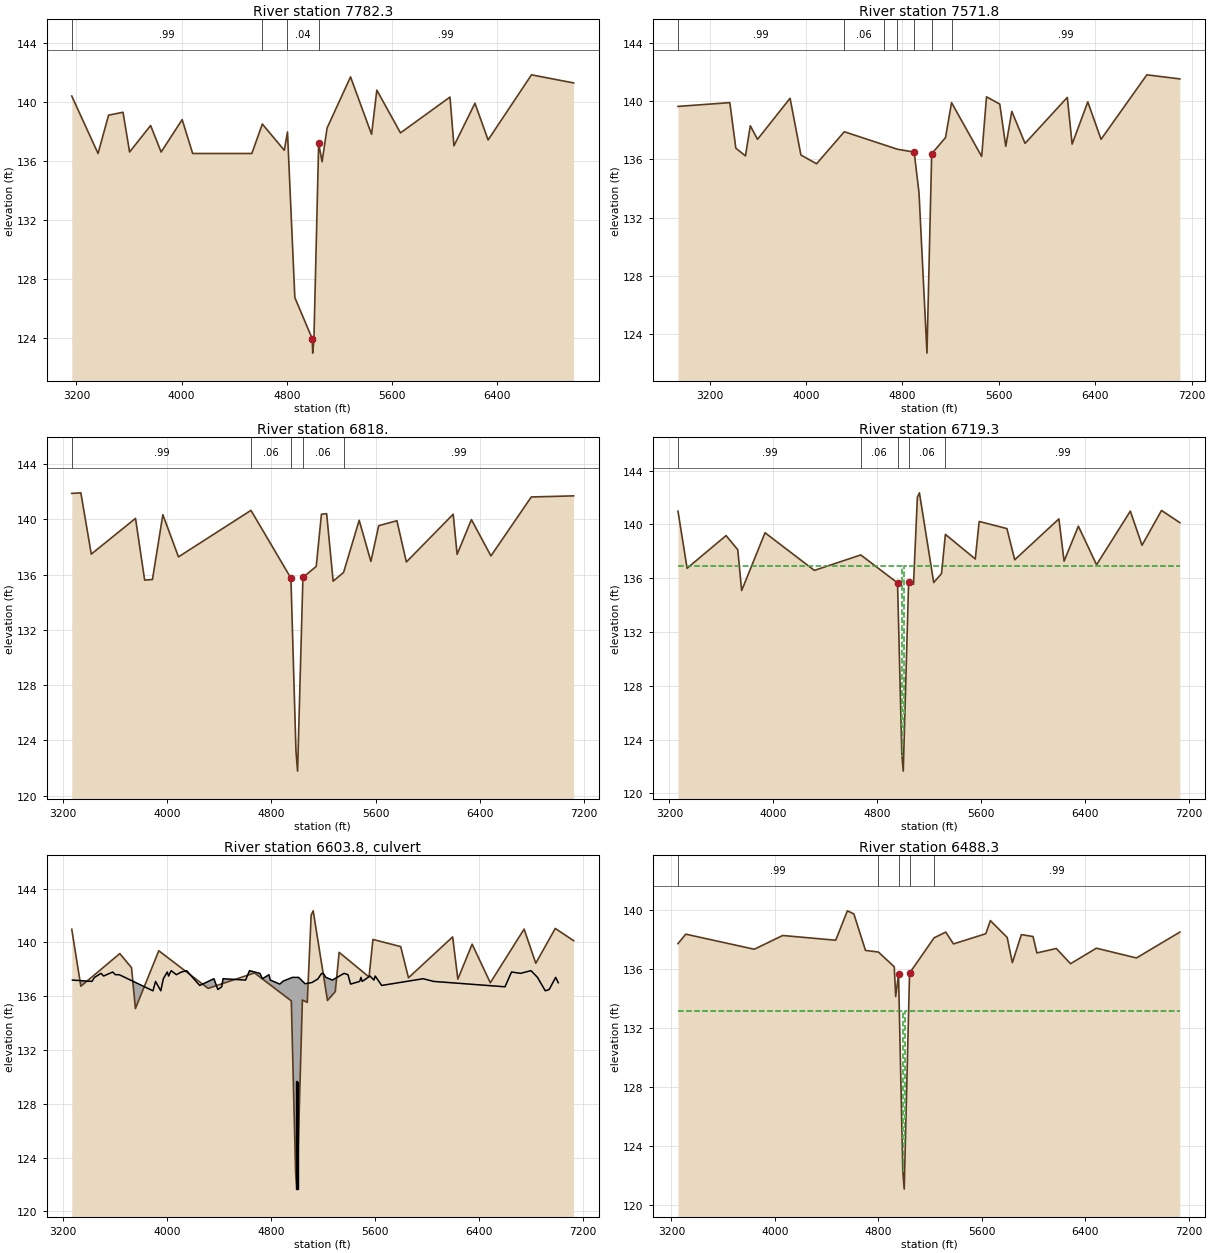
Type RM Length L Ch R = 1 ,7782.3  ,203.7,210.5,214.5
BEGIN DESCRIPTION:
Cross Section K131-04-00-X02
END DESCRIPTION:
XS GIS Cut Line= 5
      3070917.68     13951853.52       3070316.9     13950313.94
      3070185.95     13950056.88      3069857.48     13949222.65
      3068881.42     13949127.29
#Sta/Elev= 30
    3164   140.4    3364   136.5    3444   139.1    3554   139.3    3604   136.6
    3764   138.4    3844   136.6    4004   138.8    4084   136.5    4534   136.5
    4614   138.5    4781  136.72  4805.3  137.96  4861.3  126.72  4993.6  123.93
  4997.4  122.95  5006.4  123.88  5042.6  137.18  5068.6  135.94  5106.6  138.23
  5285.1   141.7  5445.1   137.8  5485.1   140.8  5665.1   137.9  6041.7  140.33
  6071.7  137.02  6231.7  139.91  6331.7  137.42  6661.7  141.84  6982.4  141.29
#Mann= 4 ,-1 , 0
    3164     .99       0    4614     .08       0  4805.3     .04       0
  5042.6     .99       0
Bank Sta=4993.6,5042.6
XS Rating Curve= 0
Exp/Cntr=.3,.1

Type RM Length L Ch R = 1 ,7571.8  ,831.6,753.8,716.7
BEGIN DESCRIPTION:
Cross Section K131-04-00_Interpolated- XS12
END DESCRIPTION:
XS GIS Cut Line= 3
      3071206.05      13951969.9      3070083.78     13949230.24
      3068886.06     13949107.64
#Sta/Elev= 30
  2937.5  139.64  3367.5   139.9  3417.5  136.77  3497.5  136.24  3537.5  138.31
  3597.5  137.38  3867.5   140.2  3957.5   136.3  4087.5   135.7  4317.5   137.9
  4647.5     137  4757.5   136.7  4897.4   136.5  4937.5   133.7  5003.5  122.69
  5042.6  136.38  5157.5   137.5  5207.5   139.9  5457.5   136.2  5497.5   140.3
  5607.5   139.8  5657.5   136.9  5707.5   139.3  5817.5   137.1  6168.1  140.26
  6208.1  137.05  6338.1  139.95  6448.1  137.38  6828.1  141.81  7102.1  141.53
#Mann= 7 ,-1 , 0
  2937.5     .99       0  4317.5     .06       0  4647.5     .08       0
  4757.5     .06       0  4897.4     .04       0  5042.6     .06       0
  5207.5     .99       0
Bank Sta=4897.4,5042.6
XS Rating Curve= 0
Exp/Cntr=.3,.1

Type RM Length L Ch R = 1 ,6818.   ,100,98.7,98
BEGIN DESCRIPTION:
K131-04-00-S8_PINELAKES -US - XS 4
END DESCRIPTION:
XS GIS Cut Line= 6
      3071969.77      13950922.4      3071262.97     13949822.97
      3070995.26     13949604.09      3070796.76     13949550.38
      3070205.76     13949209.09      3068897.33     13949074.89
#Sta/Elev= 30
  3265.5  141.89  3335.5  141.93  3415.5  137.49  3755.5  140.08  3825.5  135.61
  3885.5  135.65  3965.5  140.35  4085.5  137.29  4642.6  140.66 4949.57  135.75
 4949.62  135.73 4988.22  123.22 5000.67  121.77 5041.72   135.8    5144   136.6
    5184  140.38    5224  140.42    5274  135.53    5354  136.16    5474  139.94
    5564  136.96    5624  139.55    5764  139.91  5836.5  136.92  6196.5  140.38
  6226.5  137.47  6336.5  139.99  6486.5  137.36  6796.5  141.63  7121.8  141.71
#Mann= 5 ,-1 , 0
  3265.5     .99       0  4642.6     .06       0 4949.62     .04       0
 5041.72     .06       0    5354     .99       0
Bank Sta=4949.57,5041.72
XS Rating Curve= 0
Exp/Cntr=.5,.3

Type RM Length L Ch R = 1 ,6719.3  ,232,231,228.6
BEGIN DESCRIPTION:
Upstream Section of Bridge/Culvert/Weir
END DESCRIPTION:
XS GIS Cut Line= 6
      3071995.79     13950827.84      3071288.99     13949728.37
      3071021.28     13949509.48      3070822.78     13949455.77
      3070363.41     13949184.25      3068899.33      13949038.4
#Sta/Elev= 30
  3266.3  140.98  3336.3  136.74  3636.3  139.17  3726.3  138.12  3756.3  135.08
  3936.3  139.38  4316.3  136.58  4673.4  137.73  4956.4  135.65  4989.6  122.86
  5000.3  121.65  5041.6  135.72  5079.2  135.54  5109.2  142.03  5124.8  142.35
  5234.8  135.68  5294.8  136.34  5324.8  139.26  5554.8  137.43  5584.8  140.22
  5798.4  139.69  5858.4  137.37  6198.4  140.41  6238.4  137.27  6348.4  139.87
  6488.4     137  6748.4  140.99  6838.4  138.45  6988.4  141.04  7129.7  140.13
#Mann= 5 ,-1 , 0
  3266.3     .99       0  4673.4     .06       0  4956.4     .04       0
  5041.6     .06       0  5324.8     .99       0
#XS Ineff= 2 , 0
       0 4990.91   136.9 5009.01       0  136.93
Permanent Ineff=
       F       F
Bank Sta=4956.4,5041.6
XS Rating Curve= 0
Exp/Cntr=.5,.3

Type RM Length L Ch R = 2 ,6603.8  ,,,
BEGIN DESCRIPTION:
PINELAKES BLVD.
(named Bridgewood Valley Boulevard in old study but no such name found-VRR)
Structure ID: K131-04-00-S8
END DESCRIPTION:
Bridge Culvert--1,0,-1,-1, 0
Deck Dist Width WeirC Skew NumUp NumDn MinLoCord MaxHiCord MaxSubmerge Is_Ogee
10,211,2.6,0, 61, 61, , , .95, 0, ,,,
  3271.5  3421.5  3441.5  3491.5  3511.5  3581.5  3601.5  3631.5  3891.5  3911.5
  3951.5  3971.5  4001.5  4011.5  4031.5  4071.5  4110.8  4150.8  4250.8  4360.8
  4390.8  4420.8  4430.8  4604.5  4634.5  4714.5  4734.5  4784.5  4794.5  4867.3
  4895.2  4965.3  5012.5  5061.9  5113.2  5160.9  5188.1  5202.7  5222.7  5272.7
  5362.7  5392.7  5412.7  5482.7  5492.7  5502.1  5562.1  5592.1  5602.1  5652.1
  5971.5  6051.5  6601.5  6651.5  6721.5  6801.5  6851.5  6911.5  6941.5  6991.5
  7011.5
   137.2   137.1   137.4   137.7   137.5   137.8   137.6   137.6   136.4   137.1
   136.4   137.3   137.8   137.5   137.9   137.6   137.8   137.9   136.8   137.3
   136.5   136.7   137.3   137.2   137.9   137.7   137.3   137.6   137.2   136.9
  137.13   137.4   137.4  136.93  137.01  137.28  137.68   137.7   137.4   137.2
   137.7   137.6   136.9   137.1   137.4   137.1   137.5   137.2   137.5   136.8
   137.3   137.1   136.7   137.8   137.7   137.9   137.4   136.4   136.5   137.4
     137
                                                                                
                                                                                
                                                                                
                                                                                
                                                                                
                                                                                
        
  3271.5  3421.5  3441.5  3491.5  3511.5  3581.5  3601.5  3631.5  3891.5  3911.5
  3951.5  3971.5  4001.5  4011.5  4031.5  4071.5  4110.8  4150.8  4250.8  4360.8
  4390.8  4420.8  4430.8  4604.5  4634.5  4714.5  4734.5  4784.5  4794.5  4867.3
  4895.2  4965.3  5012.5  5061.9  5113.2  5160.9  5188.1  5202.7  5222.7  5272.7
  5362.7  5392.7  5412.7  5482.7  5492.7  5502.1  5562.1  5592.1  5602.1  5652.1
  5971.5  6051.5  6601.5  6651.5  6721.5  6801.5  6851.5  6911.5  6941.5  6991.5
  7011.5
   137.2   137.1   137.4   137.7   137.5   137.8   137.6   137.6   136.4   137.1
   136.4   137.3   137.8   137.5   137.9   137.6   137.8   137.9   136.8   137.3
   136.5   136.7   137.3   137.2   137.9   137.7   137.3   137.6   137.2   136.9
  137.13   137.4   137.4  136.93  137.01  137.28  137.68   137.7   137.4   137.2
   137.7   137.6   136.9   137.1   137.4   137.1   137.5   137.2   137.5   136.8
   137.3   137.1   136.7   137.8   137.7   137.9   137.4   136.4   136.5   137.4
     137
                                                                                
                                                                                
                                                                                
                                                                                
                                                                                
                                                                                
        
BR Coef= 1 , 0 , 0 ,1.25, 0 ,,,.8,0,2,0,
WSPro=,,,, 1 ,,,, 0 ,,,, 0 ,,,,-1 ,-1 ,-1 , 0 , 0 , 0 , 0 , 0
Culvert=2,8,8,211,.015,.5,1,8,2,121.69,4994.9,121.22,4994.9,Culvert #1  , 0 ,10
Culvert Bottom n=.015
Culvert=2,8,8,211,.015,.5,1,8,2,121.65,5005,121.21,5005,Culvert #2  , 0 ,10
Culvert Bottom n=.015
BC Design=,, 0 ,, 0 ,,,,,,
BC HTab HWMax=142.3

Type RM Length L Ch R = 1 ,6488.3  ,198.9,198.3,197.1
BEGIN DESCRIPTION:
Downstream Section of Bridge/Culvert/Weir
END DESCRIPTION:
XS GIS Cut Line= 6
      3072054.39     13950612.59      3071345.88     13949510.46
      3071072.41     13949286.87       3070872.4     13949232.75
      3070411.57     13948960.35      3068943.09     13948814.07
#Sta/Elev= 30
  3250.7  137.72  3310.7  138.36  3840.7  137.34  4060.7  138.27  4470.7  137.95
  4560.9  139.94  4610.9  139.73  4700.9  137.26  4800.9  137.15  4923.4  136.15
  4934.4  134.14  4956.4  135.65  4989.6  122.31  5000.3   121.1  5041.6  135.72
  5231.4  138.11  5321.4   138.5  5381.4   137.7  5631.4  138.39  5666.7  139.28
  5796.7  138.14  5836.7  136.43  5906.7  138.33  5996.7   138.2  6026.7  137.09
  6176.7  137.39  6286.7  136.36  6486.7  137.41  6796.7  136.75  7132.4   138.5
#Mann= 5 ,-1 , 0
  3250.7     .99       0  4800.9     .06       0  4956.4     .04       0
  5041.6     .06       0  5231.4     .99       0
#XS Ineff= 2 , 0
       0 4990.91  133.14 5009.01       0  133.14
Permanent Ineff=
       F       F
Bank Sta=4956.4,5041.6
XS Rating Curve= 0
Exp/Cntr=.5,.3