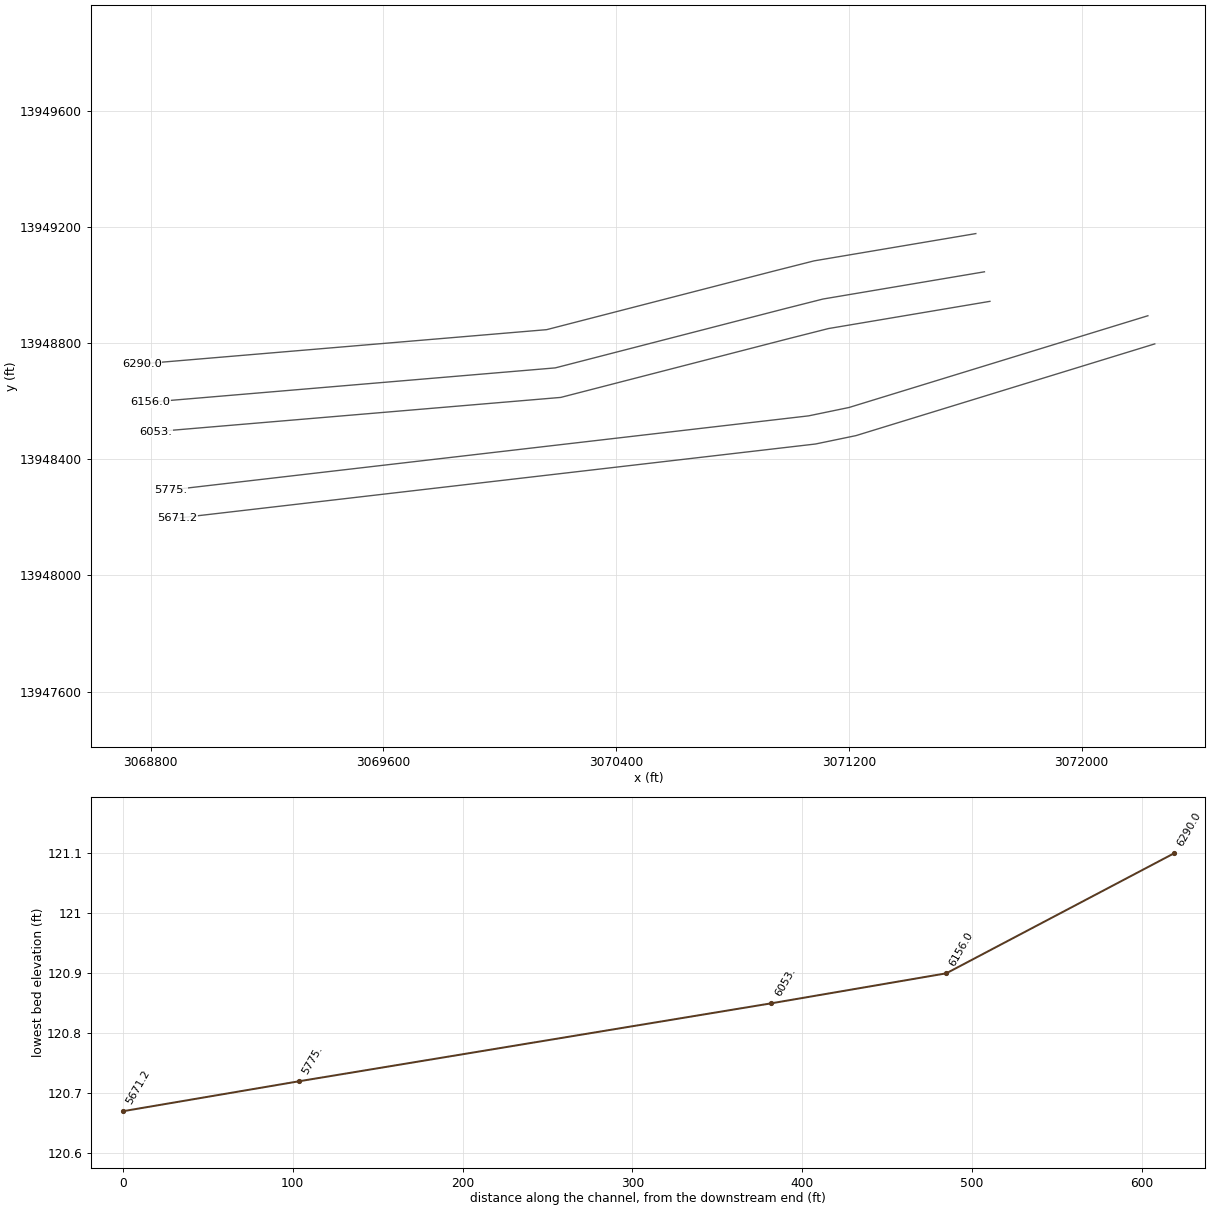
HEC-RAS study K131-04-00.prj: K131-04-00

--- K131-04-00.g01 (geometry) --- (continued)

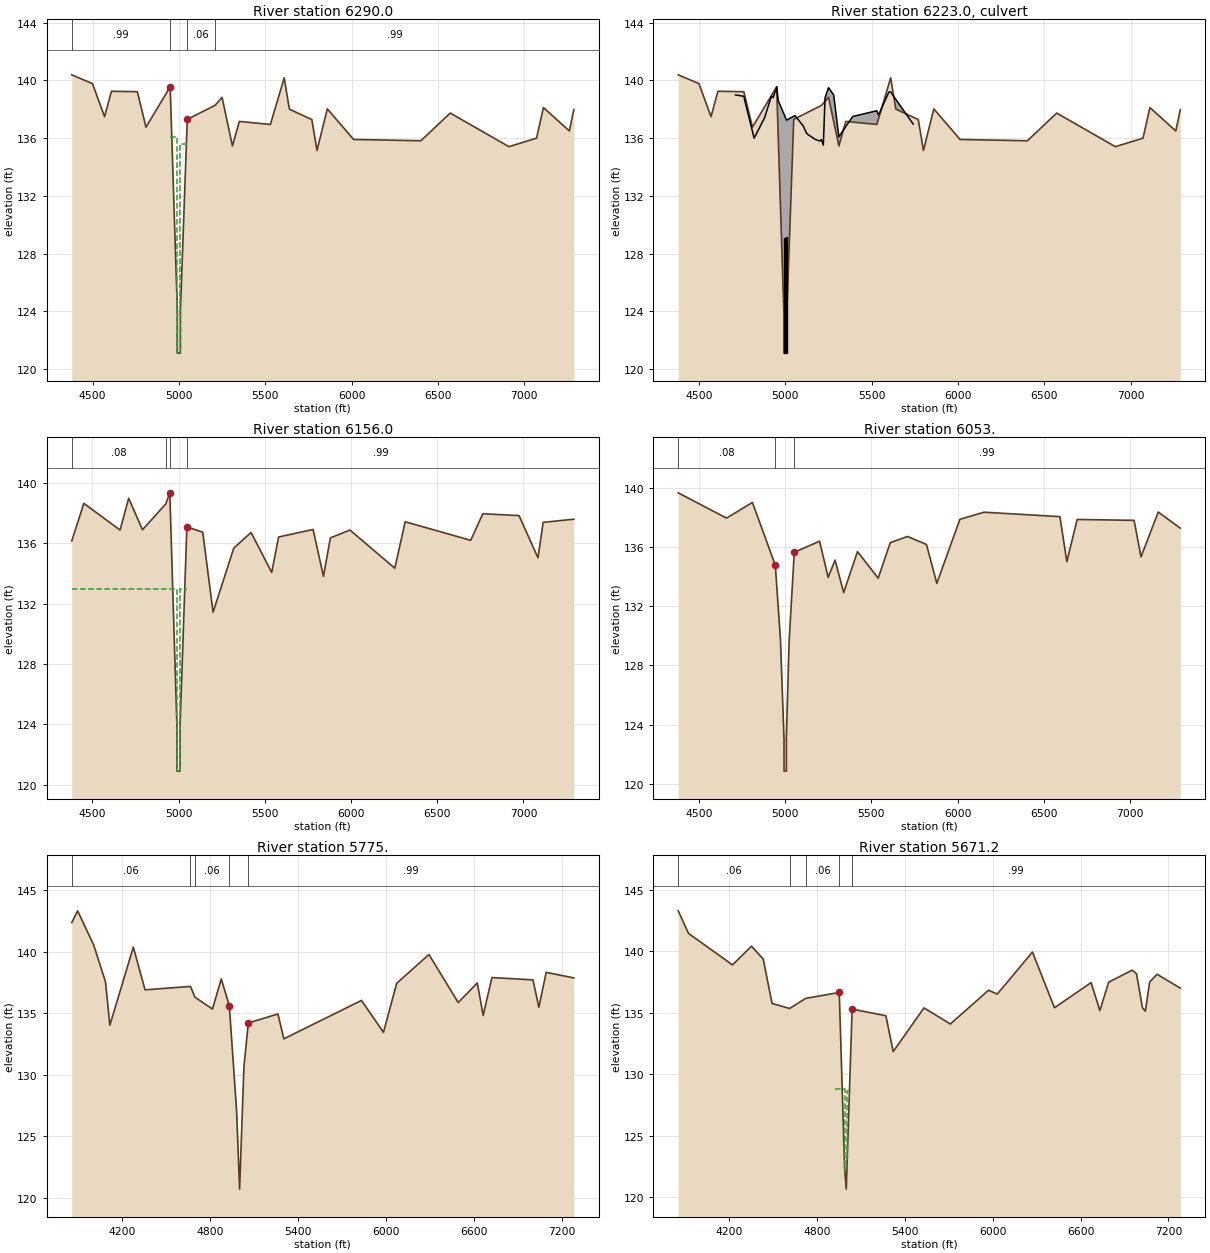
Type RM Length L Ch R = 1 ,6290.0  ,133,134,135.2
BEGIN DESCRIPTION:
Upstream Section of Bridge/Culvert/Weir
END DESCRIPTION:
XS GIS Cut Line= 5
      3071636.45     13949177.52      3071080.74     13949083.59
      3070947.57      13949049.8      3070161.14     13948846.56
      3068769.98     13948728.76
#Sta/Elev= 30
    4379  140.39    4499  139.78    4569  137.49    4609  139.25    4759  139.22
    4809  136.76  4949.3  139.56  4991.3  123.82  4991.4   121.1  5008.7   121.1
 5008.71  124.06  5048.3   137.3    5210  138.28    5250  138.83    5310  135.46
    5350  137.16    5530  136.95    5610  140.18    5640  138.01    5770  137.29
    5800  135.15    5860  138.03  6012.2  135.91  6402.2  135.82  6572.2  137.74
  6912.2  135.41  7072.2     136  7112.2  138.12  7262.2   136.5  7288.4  137.98
#Mann= 4 ,-1 , 0
    4379     .99       0  4949.3     .04       0  5048.3     .06       0
    5210     .99       0
#XS Ineff= 3 ,-1
  4949.3  4991.4  136.09  5008.7  5048.3  135.57    4379  4949.2     138
Permanent Ineff=
       F       F       F
Bank Sta=4949.3,5048.3
XS Rating Curve= 0
Exp/Cntr=.5,.3

Type RM Length L Ch R = 2 ,6223.0  ,,,
BEGIN DESCRIPTION:
Golf Cart Path 350'+/- DS OF PINELAKES BLVD
Structure ID: K131-04-00-S7
END DESCRIPTION:
Bridge Culvert--1,0,-1,-1, 0
Deck Dist Width WeirC Skew NumUp NumDn MinLoCord MaxHiCord MaxSubmerge Is_Ogee
10,114,2.6,0, 42, 42, , , .95, 0, ,,,
  4710.9  4758.7  4818.7  4878.7  4918.7  4919.4  4926.4  4929.6  4939.4 4946.56
  4949.3  4959.2  4994.2  4995.5  4996.2  4998.5  5003.6  5004.6  5005.6  5006.5
  5048.3  5055.2  5076.3  5103.3  5122.2  5131.7    5145  5171.8  5199.4  5208.6
  5219.9  5229.7    5248  5249.7  5279.7  5309.7  5389.7  5529.7  5539.7  5599.7
  5609.7  5740.2
     139   138.9     136   137.4   138.9   138.9  138.84  138.81   139.2  139.31
  139.57  138.58   137.6  137.56  137.54  137.47  137.33   137.3  137.28  137.25
  137.52  137.56  137.25  136.85  136.35  136.24  136.14  135.92   135.8   135.9
  135.52   138.8  139.44   139.5     139   136.1   137.5   137.9   137.6   139.2
   139.2  136.98
                                                                                
                                                                                
                                                                                
                                                                                
                
  4710.9  4758.7  4818.7  4878.7  4918.7  4919.4  4926.4  4929.6  4939.4 4946.56
  4949.3  4959.2  4994.2  4995.5  4996.2  4998.5  5003.6  5004.6  5005.6  5006.5
  5048.3  5055.2  5076.3  5103.3  5122.2  5131.7    5145  5171.8  5199.4  5208.6
  5219.9  5229.7    5248  5249.7  5279.7  5309.7  5389.7  5529.7  5539.7  5599.7
  5609.7  5740.2
     139   138.9     136   137.4   138.9   138.9  138.84  138.81   139.2  139.31
  139.57  138.58   137.6  137.56  137.54  137.47  137.33   137.3  137.28  137.25
  137.52  137.56  137.25  136.85  136.35  136.24  136.14  135.92   135.8   135.9
  135.52   138.8  139.44   139.5     139   136.1   137.5   137.9   137.6   139.2
   139.2  136.98
                                                                                
                                                                                
                                                                                
                                                                                
                
BR Coef= 1 , 0 , 0 ,1.25, 0 ,,,.8,0,2,0,
WSPro=,,,, 1 ,,,, 0 ,,,, 0 ,,,,-1 ,-1 ,-1 , 0 , 0 , 0 , 0 , 0
Culvert=2,8,8,114,.015,.7,1,8,2,121.11,4995.4,120.91,4995.4,Culvert #1  , 0 ,10
Culvert Bottom n=.015
Culvert=2,8,8,114,.015,.7,1,8,2,121.13,5004.7,120.91,5004.7,Culvert #2  , 0 ,10
Culvert Bottom n=.015
BC Design=,, 0 ,, 0 ,,,,,,
BC HTab HWMax=140.43

Type RM Length L Ch R = 1 ,6156.0  ,102,103,104
BEGIN DESCRIPTION:
Downstream Section of Bridge/Culvert/Weir
END DESCRIPTION:
XS GIS Cut Line= 5
      3071666.06     13949045.89      3071111.16     13948952.09
      3070978.81     13948918.51       3070190.8     13948714.86
      3068797.95     13948596.92
#Sta/Elev= 30
  4380.9  136.17  4450.9  138.66  4660.9  136.89  4710.9     139  4790.9  136.91
  4926.4  138.63  4949.3  139.36  4991.3   123.6  4991.4   120.9  5008.7   120.9
 5008.71  123.85  5048.3   137.1  5140.2  136.75  5200.2  131.44  5320.2  135.69
  5420.2  136.73  5540.2  134.08  5580.2  136.43  5780.2  136.93  5840.2  133.82
  5880.2  136.37  5994.1  136.89  6254.1  134.36  6314.1  137.44  6694.1  136.21
  6764.1  137.97  6974.1  137.85  7084.1  135.05  7114.1   137.4    7292  137.61
#Mann= 4 ,-1 , 0
  4380.9     .08       0  4926.4     .06       0  4949.3     .04       0
  5048.3     .99       0
#XS Ineff= 2 ,-1
  4380.9  4991.4     133  5008.7  5048.3     133
Permanent Ineff=
       F       F
Bank Sta=4949.3,5048.3
XS Rating Curve= 0
Exp/Cntr=.5,.3

Type RM Length L Ch R = 1 ,6053.   ,280.4,278,275.9
BEGIN DESCRIPTION:
K131-04-00-S7_GOLFCART CULVERT-DS - XS 1
END DESCRIPTION:
XS GIS Cut Line= 5
      3071684.98      13948944.1      3071130.08     13948850.39
      3070997.74     13948816.81      3070209.72     13948613.16
      3068816.87     13948495.22
#Sta/Elev= 30
  4380.1  139.66  4660.1  137.95  4810.1  139.01  4942.9  134.77  4972.9  129.71
 4993.51  122.98 4993.61  120.85 5007.23  120.85 5007.24  123.17  5022.9   129.6
  5052.9  135.64  5199.4  136.39  5249.4  133.95  5289.4  135.11  5339.4  132.92
  5419.4  135.69  5539.4  133.89  5609.4  136.29  5709.4  136.71  5819.4  136.17
  5879.4  133.54  6013.3  137.87  6153.3  138.35  6593.3  138.05  6633.3  135.01
  6693.3  137.86  7023.3   137.8  7063.3  135.33  7163.3  138.36  7291.2  137.27
#Mann= 3 ,-1 , 0
  4380.1     .08       0  4942.9     .04       0  5052.9     .99       0
Bank Sta=4942.9,5052.9
XS Rating Curve= 0
Exp/Cntr=.3,.1

Type RM Length L Ch R = 1 ,5775.   ,99.8,103.8,105
BEGIN DESCRIPTION:
K131-04-00-S6_GOLFCART CULVERT-US - XS 4
END DESCRIPTION:
XS GIS Cut Line= 4
      3072227.93      13948894.5      3071200.62     13948578.46
      3071061.72     13948549.61      3068867.83     13948294.28
#Sta/Elev= 30
  3854.6  142.37  3894.6  143.33  4004.6  140.54  4084.6  137.56  4114.6  134.04
  4274.6  140.38  4354.6  136.91  4664.6  137.19  4694.6  136.32  4814.6  135.35
  4874.6   137.8  4929.4  135.63  4979.4  127.04 4999.57  120.72  5029.4   130.7
  5059.4  134.22  5261.3  134.95  5301.3  132.93  5831.3  136.05  5981.3  133.46
  6071.3  137.44  6291.3  139.78  6491.3  135.88  6621.3  137.47  6661.3  134.84
  6721.3  137.91  7001.3  137.72  7041.3   135.5  7091.3  138.33    7280  137.88
#Mann= 5 ,-1 , 0
  3854.6     .06       0  4664.6     .08       0  4694.6     .06       0
  4929.4     .04       0  5059.4     .99       0
Bank Sta=4929.4,5059.4
XS Rating Curve= 0
Exp/Cntr=.5,.3

Type RM Length L Ch R = 1 ,5671.2  ,114,115,117.9
BEGIN DESCRIPTION:
Upstream Section of Bridge/Culvert/Weir
END DESCRIPTION:
XS GIS Cut Line= 4
      3072251.59     13948797.53      3071224.27     13948481.49
      3071085.37     13948452.64      3068891.48     13948197.31
#Sta/Elev= 30
  3855.4  143.27  3925.4  141.44  4225.4  138.88  4355.4   140.4  4435.4  139.35
  4495.4  135.75  4615.4  135.34  4725.4  136.16    4954  136.64    4991  122.25
  5001.8  120.67  5041.7  135.29  5272.1  134.75  5322.1  131.84  5532.1  135.39
  5712.1  134.08  5972.1  136.82  6032.1  136.51  6272.1  139.92  6422.1   135.4
  6672.1  137.44  6732.1  135.17  6792.1  137.48  6952.1  138.45  6982.1  138.16
  7022.1  135.41  7042.1  135.12  7072.1   137.5  7122.1  138.12  7280.8  136.99
#Mann= 5 ,-1 , 0
  3855.4     .06       0  4615.4     .08       0  4725.4     .06       0
    4954     .04       0  5041.7     .99       0
#XS Ineff= 2 ,-1
 4925.74 4991.56  128.84 5008.39  5041.7  128.67
Permanent Ineff=
       F       F
Bank Sta=4954,5041.7
XS Rating Curve= 0
Exp/Cntr=.5,.3