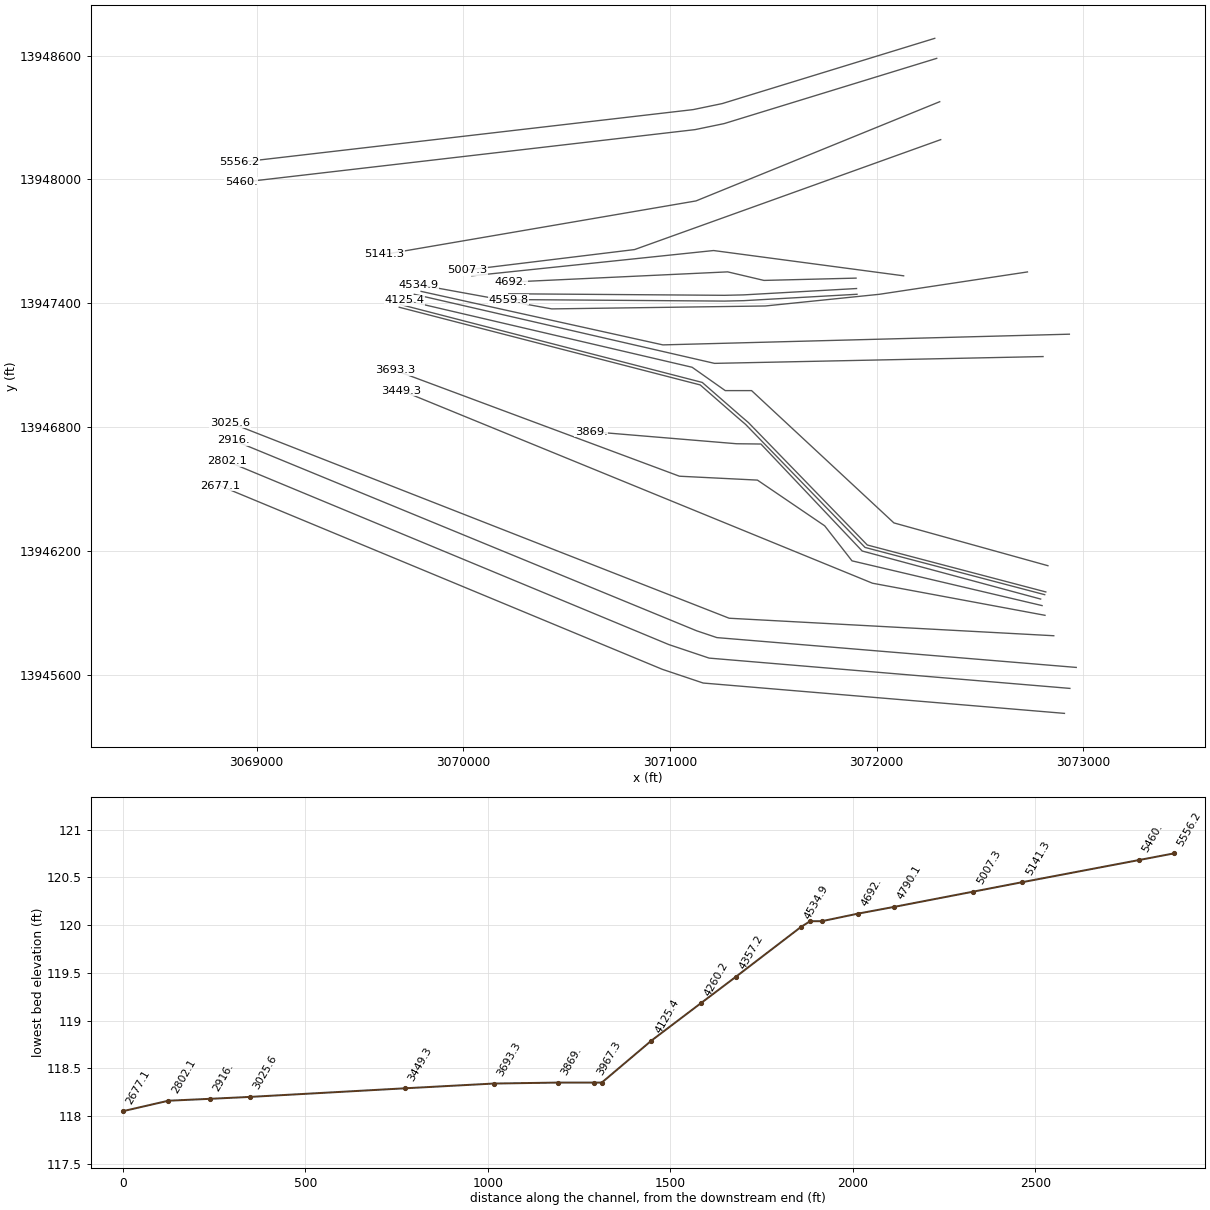
HEC-RAS study K131-04-00.prj: K131-04-00

--- K131-04-00.g01 (geometry) --- (continued)

Type RM Length L Ch R = 2 ,5613.7  ,,,
BEGIN DESCRIPTION:
Golf Cart Path 950'+/- DS OF PINELAKES BLVD
Structure ID: K131-04-00-S6
END DESCRIPTION:
Bridge Culvert--1,0,-1,-1, 0
Deck Dist Width WeirC Skew NumUp NumDn MinLoCord MaxHiCord MaxSubmerge Is_Ogee
10,95,2.6,0, 35, 36, , , .95, 0, ,,,
  4725.3  4757.5  4777.5  4804.4  4807.5    4817  4824.4  4834.4  4836.8  4867.7
  4913.5  4917.4    4954  4966.1    4991  4995.3  4996.6  5001.8    5004  5004.6
  5005.4    5016  5031.4  5041.7  5057.3  5060.2  5075.2  5083.1  5113.1  5163.9
  5212.4  5214.4  5217.7  5265.9  5274.2
     136   136.3   135.7  135.98  136.01   132.4   132.4     133  132.94   135.4
  136.56  136.57  136.65  136.34  136.22   136.2  136.19  136.17  136.16  136.15
  136.15   136.1  136.27   136.2  136.09  136.07  135.65  135.39  135.28   135.1
  134.93  134.92  134.91  134.73   134.3
                                                                                
                                                                                
                                                                                
                                        
  4725.3  4757.5  4777.5  4804.4  4807.5    4817  4824.4  4834.4  4836.8  4867.7
  4913.5  4917.4    4954  4966.1    4991  4995.3  4996.6  5001.8    5004  5004.6
  5005.4    5016  5031.4  5041.7  5057.3  5060.2  5075.2  5083.1  5113.1  5163.9
  5212.4  5214.4  5217.7  5265.9  5274.2  5304.2
     136   136.3   135.7  135.98  136.01   132.4   132.4     133  132.94   135.4
  136.56  136.57  136.65  136.34  136.22   136.2  136.19  136.17  136.16  136.15
  136.15   136.1  136.27   136.2  136.09  136.07  135.65  135.39  135.28   135.1
  134.93  134.92  134.91  134.73   134.3   132.5
                                                                                
                                                                                
                                                                                
                                                
BR Coef= 1 , 0 , 0 ,1.25, 0 ,,,.8,0,2,0,
WSPro=,,,, 1 ,,,, 0 ,,,, 0 ,,,,-1 ,-1 ,-1 , 0 , 0 , 0 , 0 , 0
Culvert=2,8,8,95,.015,.7,1,8,2,120.84,4995.6,120.86,4995.6,Culvert #1  , 0 ,10
Culvert Bottom n=.015
Culvert=2,8,8,95,.015,.7,1,8,2,120.67,5004.4,120.91,5004.4,Culvert #2  , 0 ,10
Culvert Bottom n=.015
BC Design=,, 0 ,, 0 ,,,,,,
BC HTab HWMax=140.47

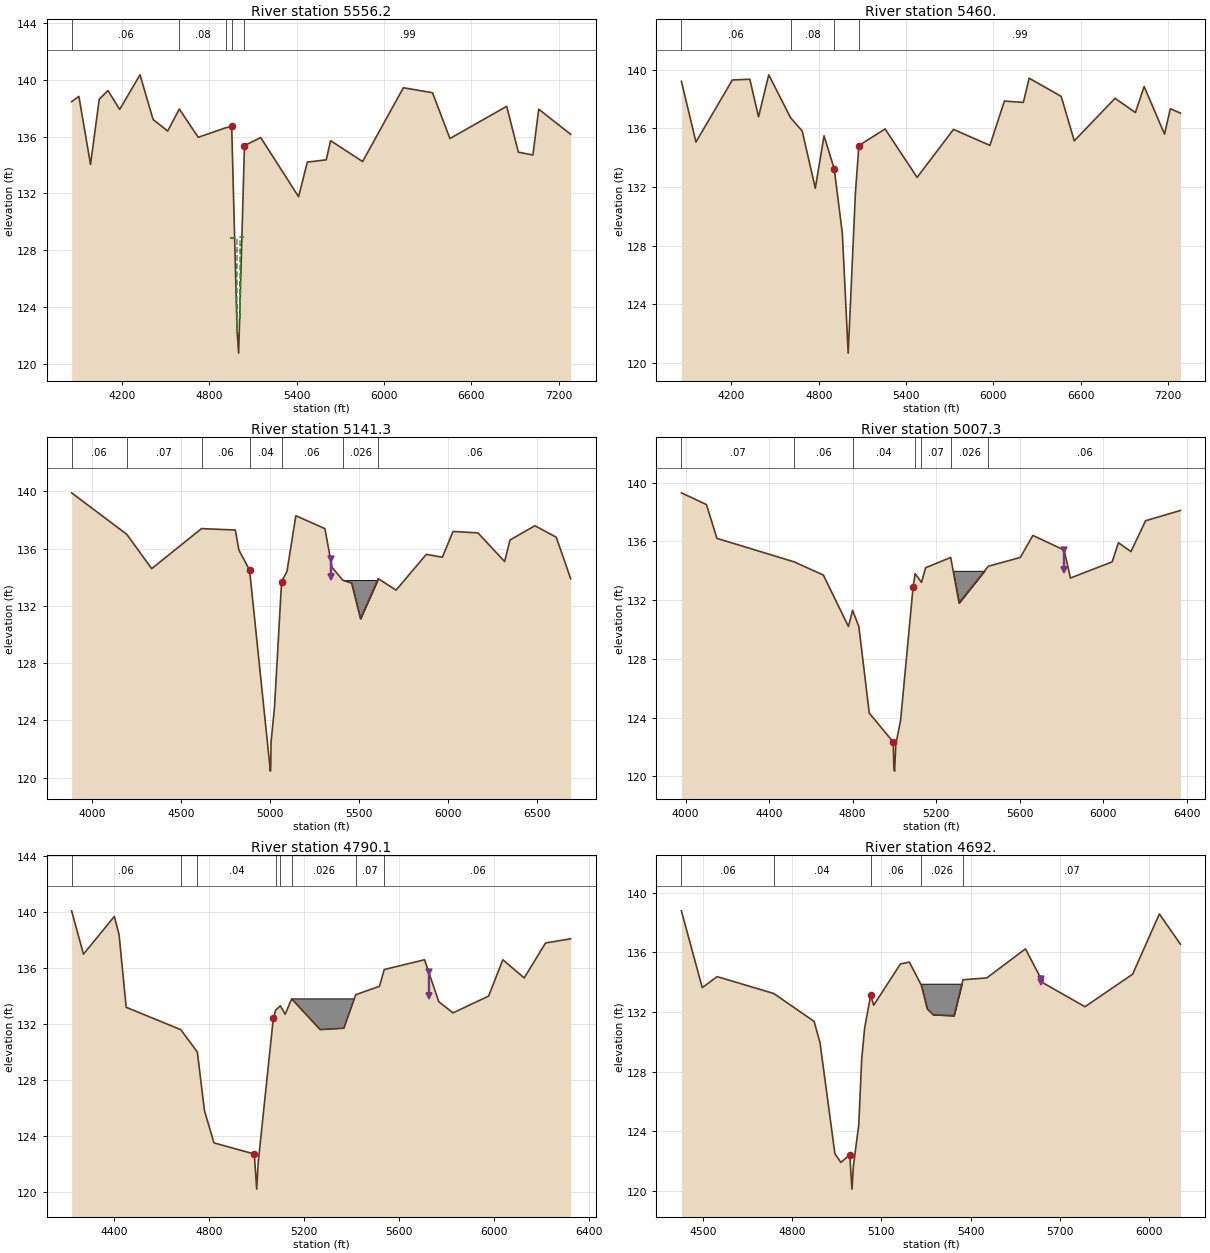
Type RM Length L Ch R = 1 ,5556.2  ,95,96.2,98
BEGIN DESCRIPTION:
Downstream Section of Bridge/Culvert/Weir
END DESCRIPTION:
XS GIS Cut Line= 4
      3072280.73     13948683.93      3071252.52     13948367.62
      3071111.83     13948338.39      3068917.06     13948082.96
#Sta/Elev= 30
  3854.1  138.47  3904.1  138.84  3984.1  134.05  4044.1  138.65  4104.1  139.25
  4184.1  137.92  4324.1  140.36  4414.1  137.21  4514.1   136.4  4594.1  137.95
  4724.1  135.96  4913.5  136.63    4954  136.72    4991  122.33  5001.8  120.75
  5041.7  135.37  5153.6  135.94  5413.6  131.77  5473.6  134.21  5603.6  134.37
  5633.6  135.72  5853.6  134.25  6133.6  139.45  6333.6   139.1  6453.6  135.87
  6843.6  138.14  6923.6  134.91  7023.6  134.71  7063.6  137.94  7283.1  136.17
#Mann= 5 ,-1 , 0
  3854.1     .06       0  4594.1     .08       0  4913.5     .06       0
    4954     .04       0  5041.7     .99       0
#XS Ineff= 2 ,-1
 4940.14 4991.57  128.86 5008.39  5041.7  128.91
Permanent Ineff=
       F       F
Bank Sta=4954,5041.7
XS Rating Curve= 0
Exp/Cntr=.5,.3

Type RM Length L Ch R = 1 ,5460.   ,305.2,318.7,325.9
BEGIN DESCRIPTION:
K131-04-00-S6_GOLFCART CULVERT-DS - XS 1
END DESCRIPTION:
XS GIS Cut Line= 4
      3072290.19      13948586.9      3071261.98     13948270.65
      3071121.29     13948241.43      3068926.52     13947985.99
#Sta/Elev= 30
  3855.9  139.21  3955.9  135.07  4205.9   139.3  4325.9  139.35  4385.9  136.79
  4455.9  139.65  4605.9  136.73  4685.9  135.82  4775.9  131.92  4835.9  135.49
  4905.9  133.24  4961.7  128.85  5001.8  120.68  5051.7  131.63  5075.4  134.83
  5255.4  135.96  5475.4  132.66  5725.4  135.93  5975.4  134.84  6075.4  137.86
  6205.4  137.77  6245.4  139.42  6465.4  138.18  6555.4  135.15  6835.4  138.05
  6975.4  137.08  7035.4  138.85  7175.4  135.61  7215.4  137.34  7284.9  137.04
#Mann= 4 ,-1 , 0
  3855.9     .06       0  4605.9     .08       0  4905.9     .04       0
  5075.4     .99       0
Bank Sta=4905.9,5075.4
XS Rating Curve= 0
Exp/Cntr=.3,.1

Type RM Length L Ch R = 1 ,5141.3  ,135,134,129.4
BEGIN DESCRIPTION:
Cross Section K131-04-00_Interpolated- XS11; Detention pond on right VRR
END DESCRIPTION:
XS GIS Cut Line= 3
      3072304.74     13948376.75      3071125.89     13947895.78
      3069616.95     13947636.43
#Sta/Elev= 30
  3884.8   139.9  4194.8     137  4334.8   134.6  4614.8   137.4  4804.8   137.3
  4824.8   135.9  4884.8   134.5  5001.8120.4489    5004120.8488  5005.4122.4489
  5024.8   124.9  5064.8   133.7  5094.8   134.4  5144.8   138.3    5308   137.4
    5348   134.7    5408   133.8    5458   133.6    5508   131.1    5608   133.9
    5708   133.1    5878   135.6    5968   135.4    6028   137.2    6168   137.1
    6318   135.1    6348   136.6    6488   137.6    6608   136.8  6689.1   133.9
#Mann= 7 ,-1 , 0
  3884.8     .06       0  4194.8     .07       0  4614.8     .06       0
  4884.8     .04       0  5064.8     .06       0    5408    .026       0
    5608     .06       0
Levee=0,,,-1,5339.78,134.02,,
#Block Obstruct= 1 ,-1
    5308    5615   133.8
Bank Sta=4884.8,5064.8
XS Rating Curve= 0
Exp/Cntr=.3,.1

Type RM Length L Ch R = 1 ,5007.3  ,248.2,217.2,187.6
BEGIN DESCRIPTION:
Cross Section K131-04-00_Interpolated- XS10
END DESCRIPTION:
XS GIS Cut Line= 3
      3072309.46     13948192.85      3070828.82     13947660.01
      3070017.76     13947560.98
#Sta/Elev= 30
  3980.2   139.3  4100.2   138.5  4150.2   136.2  4520.2   134.6  4660.2   133.7
  4780.2   130.2  4800.2   131.3  4830.2   130.2  4880.2   124.3  4995.1  122.33
  4997.7  120.66  5001.4  120.35  5007.4  122.19  5030.2   123.8  5090.2   132.9
  5100.2   133.8  5130.2   133.2  5150.2   134.2  5270.2   134.9  5310.2   131.8
  5450.2   134.3  5603.8   134.9  5663.8   136.4  5813.8   135.4  5843.8   133.5
  6043.8   134.6  6073.8   135.9  6133.8   135.3  6203.8   137.4  6370.9   138.1
#Mann= 7 ,-1 , 0
  3980.2     .07       0  4520.2     .06       0  4800.2     .04       0
  5100.2     .06       0  5130.2     .07       0  5270.2    .026       0
  5450.2     .06       0
Levee=0,,,-1,5814.13,134.02,,
#XS Ineff= 2 , 0
       0                    5688       0     134
Permanent Ineff=
       F       F
#Block Obstruct= 1 ,-1
 5268.68  5452.3  133.99
Bank Sta=4995.1,5090.2
XS Rating Curve= 0
Exp/Cntr=.3,.1

Type RM Length L Ch R = 1 ,4790.1  ,105.9,98.1,94.6
BEGIN DESCRIPTION:
Cross Section K131-04-00_Interpolated- XS9; Detention pond on right VRR
END DESCRIPTION:
XS GIS Cut Line= 3
      3072130.27     13947532.69      3071210.77     13947655.29
      3070041.34     13947532.69
#Sta/Elev= 30
  4221.3   140.1  4271.3     137  4401.3   139.7  4421.3   138.4  4451.3   133.2
  4681.3   131.6  4751.3     130  4781.3   125.8  4821.3   123.5  4991.3   122.7
  5001.4  120.19  5007.4  122.03  5071.3   132.4  5081.3     133  5101.3   133.3
  5121.3   132.7  5148.9   133.8  5268.9   131.6  5368.9   131.7  5418.9   134.1
  5518.9   134.7  5538.9   135.9  5708.9   136.6  5768.9   133.6  5828.9   132.8
  5978.9     134  6038.9   136.6  6128.9   135.3  6218.9   137.8  6324.8   138.1
#Mann= 8 ,-1 , 0
  4221.3     .06       0  4681.3     .06       0  4751.3     .04       0
  5081.3     .06       0  5101.3     .07       0  5148.9    .026       0
  5418.9     .07       0  5538.9     .06       0
Levee=0,,,-1,5725.92,134.04,,
#Block Obstruct= 1 ,-1
 5148.86    5419   133.8
Bank Sta=4991.3,5071.3
XS Rating Curve= 0
Exp/Cntr=.3,.1

Type RM Length L Ch R = 1 ,4692.   ,84.8,100.2,111.2
BEGIN DESCRIPTION:
K131-04-00-S5_WOOD GOLFCART BRIDGE -US - XS 4
END DESCRIPTION:
XS GIS Cut Line= 4
      3071900.09      13947521.6      3071454.54     13947510.43
      3071279.05     13947551.87      3070229.37     13947502.49
#Sta/Elev= 30
  4428.3  138.78  4498.3  133.63  4548.3  134.37  4738.3  133.24    4874  131.37
    4894  129.94    4944   122.5    4964  121.91    4994  122.42  5001.4  120.12
 5006.14  121.67  5024.2  124.43    5034  128.82    5044  130.93  5064.3  133.12
  5074.3  132.45  5164.3  135.22  5194.3  135.34  5234.3   133.8  5254.3   132.2
  5274.3  131.81  5344.3  131.75  5374.3  134.16  5454.3  134.28  5584.3  136.23
  5644.3  133.94  5784.3  132.35  5944.3  134.53  6034.3  138.57  6105.1  136.54
#Mann= 5 ,-1 , 0
  4428.3     .06       0  4738.3     .04       0  5064.3     .06       0
  5234.3    .026       0  5374.3     .07       0
Levee=0,,,-1,5637,134,,
#Block Obstruct= 1 ,-1
 5192.775487.972 133.894
Bank Sta=4994,5064.3
XS Rating Curve= 0
Exp/Cntr=.5,.3

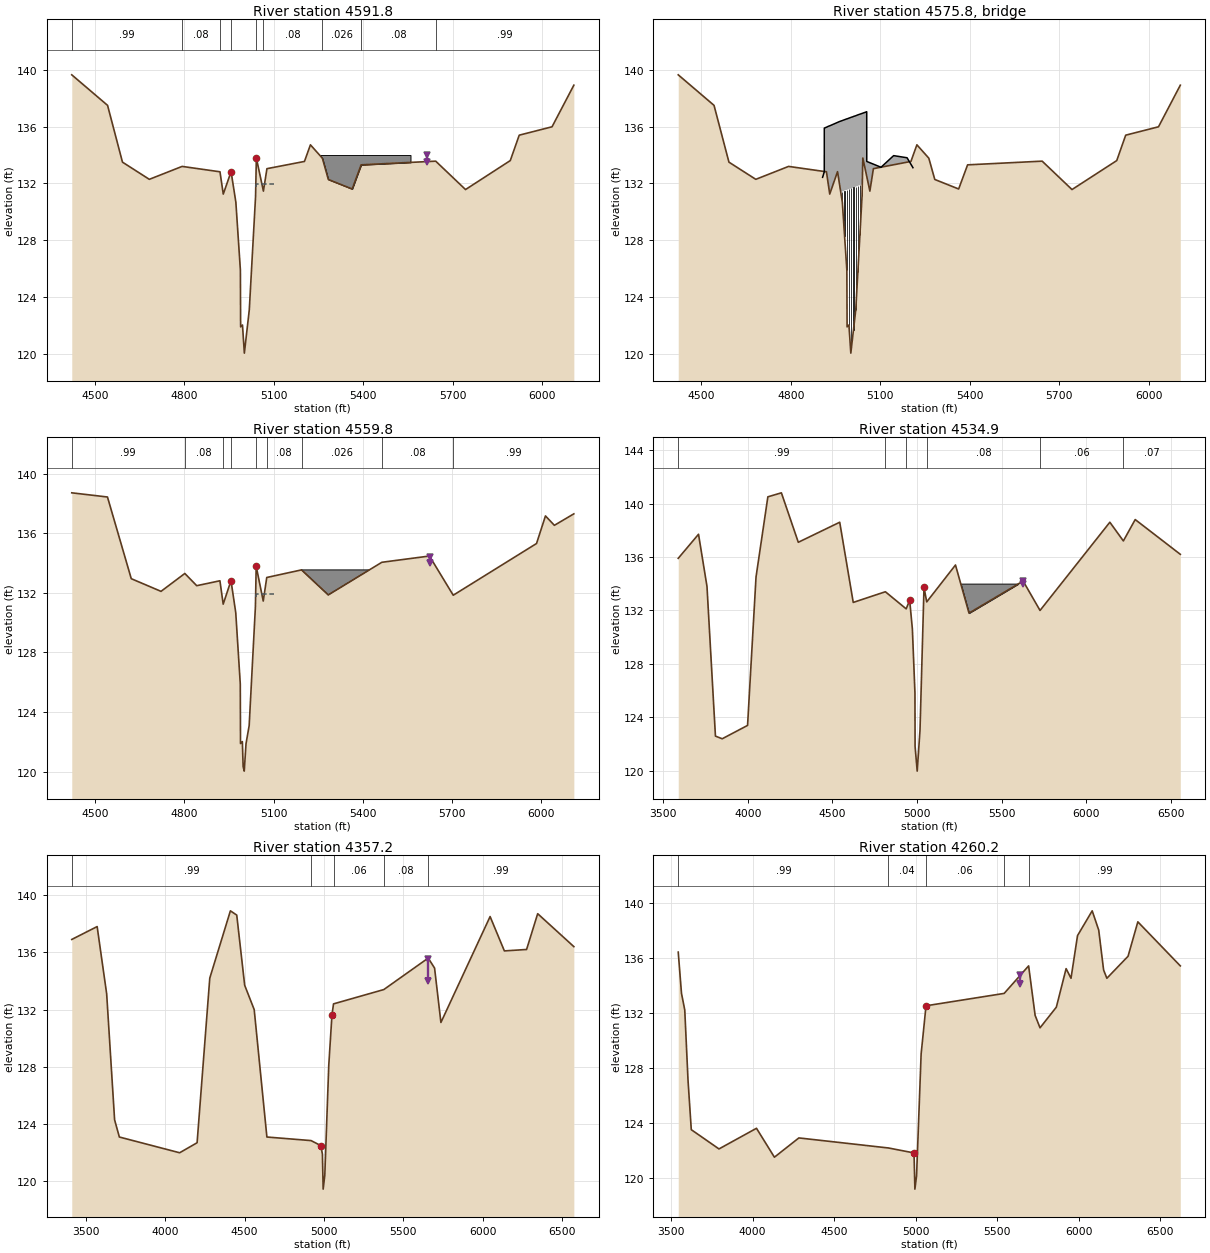
Type RM Length L Ch R = 1 ,4591.8  ,33,32,28
BEGIN DESCRIPTION:
Upstream Section of Bridge/Culvert/Weir
END DESCRIPTION:
XS GIS Cut Line= 4
      3071902.36      13947471.1      3071355.77     13947440.28
      3071263.16      13947438.2       3070220.1      13947445.7
#Sta/Elev= 30
  4422.8  139.64  4542.8  137.49  4592.8  133.49  4682.8  132.28  4792.8  133.19
  4919.7  132.81  4930.7  131.24  4956.9  132.82  4972.9  130.67  4988.1  125.89
  4988.9  121.89  4995.1  122.02  5001.4  120.04    5018   123.1    5039  131.08
  5041.6  133.78  5065.3  131.45  5077.1  133.03  5202.9  133.54  5222.9  134.71
  5262.9  133.77  5282.9  132.27  5362.9   131.6  5392.9   133.3  5642.9  133.56
  5742.9  131.56  5892.9   133.6  5922.9  135.39  6032.9  135.98    6106  138.91
#Mann= 9 ,-1 , 0
  4422.8     .99       0  4792.8     .08       0  4919.7     .06       0
  4956.9     .04       0  5041.6     .06       0  5065.3     .08       0
  5262.9    .026       0  5392.9     .08       0  5642.9     .99       0
Levee=0,,,-1,5613.5,133.99,,
#XS Ineff= 2 ,-1
  4801.1 4967.39  131.41 5039.63    5100  131.93
Permanent Ineff=
       F       F
#Block Obstruct= 1 ,-1
 5237.62 5558.42  133.99
Bank Sta=4956.9,5041.6
XS Rating Curve= 0
Exp/Cntr=.5,.3

Type RM Length L Ch R = 3 ,4575.8  ,,,
BEGIN DESCRIPTION:
Golf Cart Path 1900' DS PINELAKES BLVD
Structure ID: K131-04-00-S5
END DESCRIPTION:
Bridge Culvert--1,0,-1,-1, 0
Deck Dist Width WeirC Skew NumUp NumDn MinLoCord MaxHiCord MaxSubmerge Is_Ogee
10,12,2.6,0, 45, 45, , , .95, 0, ,,,
 4906.76 4912.39  4912.5 4912.61  4919.7  4926.5  4930.7  4936.2  4956.9 4964.59
  4964.7 4964.81 4967.41  4967.5  4972.9  4980.5  4988.1  4988.9  4995.1  4996.2
  4997.7  5001.4  5002.7  5003.9  5007.4 5008.29  5008.4 5008.51  5010.5    5018
    5025  5031.9    5039 5039.71 5039.82  5041.6 5054.59  5054.7 5054.81  5065.3
  5077.1  5102.6  5144.9  5189.9  5209.7
  132.42  132.81  135.89  135.89  135.95  136.02  136.05   136.1  136.29  136.36
  136.36  136.36  136.38  136.38  136.42  136.48  136.54  136.54  136.59   136.6
  136.61  136.64  136.65  136.66  136.68  136.69  136.69  136.69  136.71  136.76
  136.82  136.87  136.92  136.93  136.93  136.94  137.04  137.04  133.54  133.45
  133.35  133.13  133.95   133.8   133.1
                                                                                
          131.76  131.41   131.4  131.42  131.48  131.54  131.54  131.59   131.6
  131.61  131.64  131.65  131.66  131.68  131.69  131.69  131.69  131.71  131.76
  131.82  131.87  131.92  131.93  131.93
                                        
 4906.76 4912.39  4912.5 4912.61  4919.7  4926.5  4930.7  4936.2  4956.9 4964.59
  4964.7 4964.81 4967.41  4967.5  4972.9  4980.5  4988.1  4988.9  4995.1  4996.2
  4997.7  5001.4  5002.7  5003.9  5007.4 5008.29  5008.4 5008.51  5010.5    5018
    5025  5031.9    5039 5039.71 5039.82  5041.6 5054.59  5054.7 5054.81  5065.3
  5077.1  5102.6  5144.9  5189.9  5209.7
  132.42  132.81  135.89  135.89  135.95  136.02  136.05   136.1  136.29  136.36
  136.36  136.36  136.38  136.38  136.42  136.48  136.54  136.54  136.59   136.6
  136.61  136.64  136.65  136.66  136.68  136.69  136.69  136.69  136.71  136.76
  136.82  136.87  136.92  136.93  136.93  136.94  137.04  137.04  133.54  133.45
  133.35  133.13  133.95   133.8   133.1
                                                                                
          131.76  131.41   131.4  131.42  131.48  131.54  131.54  131.59   131.6
  131.61  131.64  131.65  131.66  131.68  131.69  131.69  131.69  131.71  131.76
  131.82  131.87  131.92  131.93  131.93
                                        
Pier Skew, UpSta & Num, DnSta & Num=  ,4972.9, 2 ,4972.9, 2 , 0 , 0 , 0 ,,
       1       1
   129.5  132.42
       1       1
   129.5  132.42
Pier Skew, UpSta & Num, DnSta & Num=  ,4980.5, 2 ,4980.5, 2 , 0 , 0 , 0 ,,
       1       1
  126.99  132.48
       1       1
  126.99  132.48
Pier Skew, UpSta & Num, DnSta & Num=  ,4988.1, 2 ,4988.1, 2 , 0 , 0 , 0 ,,
       1       1
  122.39  132.54
       1       1
  122.39  132.54
Pier Skew, UpSta & Num, DnSta & Num=  ,4995.1, 2 ,4995.1, 2 , 0 , 0 , 0 ,,
       1       1
  120.55  132.59
       1       1
  120.55  132.59
Pier Skew, UpSta & Num, DnSta & Num=  ,5002.7, 2 ,5002.7, 2 , 0 , 0 , 0 ,,
       1       1
  119.58  132.65
       1       1
  119.58  132.65
Pier Skew, UpSta & Num, DnSta & Num=  ,5010.4, 2 ,5010.4, 2 , 0 , 0 , 0 ,,
       1       1
  120.65  132.71
       1       1
  120.65  132.71
Pier Skew, UpSta & Num, DnSta & Num=  ,5018, 2 ,5018, 2 , 0 , 0 , 0 ,,
       1       1
     122  132.76
       1       1
     122  132.76
Pier Skew, UpSta & Num, DnSta & Num=  ,5025, 2 ,5025, 2 , 0 , 0 , 0 ,,
       1       1
  124.77  132.82
       1       1
  124.77  132.82
Pier Skew, UpSta & Num, DnSta & Num=  ,5031.9, 2 ,5031.9, 2 , 0 , 0 , 0 ,,
       1       1
  127.35  132.87
       1       1
  127.35  132.87
Pier Skew, UpSta & Num, DnSta & Num=  ,5039, 2 ,5039, 2 , 0 , 0 , 0 ,,
       1       1
   129.9  132.93
       1       1
   129.9  132.93
BR Coef= 1 , 1 , 1 ,1.25, 0 ,,,.8,0,2,0,
WSPro=,,,, 1 ,,,, 0 ,,,, 0 ,,,,-1 ,-1 ,-1 , 0 , 0 , 0 , 0 , 0
BC Design=,, 0 ,, 0 ,,,,,,
BC HTab HWMax=140.21

Type RM Length L Ch R = 1 ,4559.8  ,28,24.9,23
BEGIN DESCRIPTION:
Downstream Section of Bridge/Culvert/Weir
END DESCRIPTION:
XS GIS Cut Line= 4
      3071904.63     13947443.26      3071356.88      13947412.3
      3071263.37      13947410.2      3070217.95     13947417.74
#Sta/Elev= 30
  4421.7  138.71  4541.7  138.43  4621.7  132.95  4721.7   132.1  4801.7   133.3
  4841.7  132.48  4919.7  132.81  4930.7  131.24  4956.9  132.82  4972.9  130.67
  4988.1  125.89  4988.9  121.89  4995.1  122.02  4997.7  120.35  5001.4  120.04
  5007.4  121.88    5018   123.1    5039  131.08  5041.6  133.78  5065.3  131.45
  5077.1  133.03  5193.9  133.54  5283.9  131.86  5463.9  134.05  5623.9  134.47
  5703.9  131.84  5983.9  135.31  6013.9  137.16  6043.9  136.53  6109.3   137.3
#Mann= 9 ,-1 , 0
  4421.7     .99       0  4801.7     .08       0  4930.7     .06       0
  4956.9     .04       0  5041.6     .06       0  5077.1     .08       0
  5193.9    .026       0  5463.9     .08       0  5703.9     .99       0
Levee=0,,,-1,5626.46,134.02,,
#XS Ineff= 2 ,-1
 5039.63    5100  131.93  4801.1 4967.39  131.41
Permanent Ineff=
       F       F
#Block Obstruct= 1 ,-1
    5193 5560.04  133.54
Bank Sta=4956.9,5041.6
XS Rating Curve= 0
Exp/Cntr=.5,.3

Type RM Length L Ch R = 1 ,4534.9  ,176,177.7,179
BEGIN DESCRIPTION:
Cross Section K131-04-00_Interpolated- XS8; Online detention pond on left VRR
END DESCRIPTION:
XS GIS Cut Line= 5
      3072729.13     13947551.55      3072012.39      13947443.1
      3071460.68     13947386.51      3070428.01     13947372.37
      3069781.99     13947490.25
#Sta/Elev= 30
  3588.3   135.9  3708.3   137.7  3758.3   133.8  3808.3   122.6  3848.3   122.4
  3998.3   123.4  4048.3   134.5  4118.3   140.5  4198.3   140.8  4298.3   137.1
  4543.2   138.6  4623.2   132.6  4813.2   133.4  4936.2  132.12  4956.9  132.76
  4972.9  130.61  4988.1  125.83  4988.9  121.83  5001.4  119.98    5018  123.04
  5041.6  133.72  5057.8  132.64  5227.8   135.4  5307.8   131.8  5627.8   134.2
  5727.8     132  6140.6   138.6  6220.6   137.2  6290.6   138.8  6557.3   136.2
#Mann= 6 ,-1 , 0
  3588.3     .99       0  4813.2     .08       0  4936.2     .04       0
  5057.8     .08       0  5727.8     .06       0  6220.6     .07       0
Levee=0,,,-1,5626.46,133.97,,
#Block Obstruct= 2 ,-1
 5251.58 5598.11  134.01          6557.3  131.77
Bank Sta=4956.9,5041.6
XS Rating Curve= 0
Exp/Cntr=.3,.1

Type RM Length L Ch R = 1 ,4357.2  ,98,97,96.6
BEGIN DESCRIPTION:
Cross Section K131-04-00_Interpolated- XS7
END DESCRIPTION:
XS GIS Cut Line= 3
      3072931.89     13947249.76      3070965.56      13947197.9
      3069796.14     13947457.24
#Sta/Elev= 30
  3410.6   136.9  3570.6   137.8  3630.6   133.1  3680.6   124.3  3710.6   123.1
  4090.6     122  4200.6   122.7  4280.6   134.2  4410.6   138.9  4450.6   138.6
  4500.6   133.7  4560.6     132  4640.6   123.1    4919  122.85  4980.6   122.5
  4990.6   121.9 4995.32  119.46 5005.62  120.43  5030.6   128.1  5050.6   131.6
  5060.6   132.4  5377.6   133.4  5657.6   135.6  5697.6   134.9  5737.6   131.1
  6047.6   138.5  6137.6   136.1  6277.6   136.2  6347.6   138.7  6575.5   136.4
#Mann= 5 ,-1 , 0
  3410.6     .99       0    4919     .04       0  5060.6     .06       0
  5377.6     .08       0  5657.6     .99       0
Levee=0,,,-1,5653.47,134,,
Bank Sta=4980.6,5050.6
XS Rating Curve= 0
Exp/Cntr=.3,.1

Type RM Length L Ch R = 1 ,4260.2  ,135.7,134.8,133.9
BEGIN DESCRIPTION:
Cross Section K131-04-00_Interpolated- XS6
END DESCRIPTION:
XS GIS Cut Line= 3
      3072804.58     13947141.31      3071215.48      13947108.3
      3069763.13      13947443.1
#Sta/Elev= 30
  3543.6   136.4  3563.6   133.4  3583.6   132.2  3603.6   127.1  3623.6   123.5
  3793.6   122.1  4023.6   123.6  4133.6   121.5  4283.6   122.9    4833  122.17
 4990.02  121.81 4995.32  119.18 5005.62  120.15  5033.6     129  5063.6   132.5
    5543   133.4    5693   135.4    5733   131.8    5763   130.9    5863   132.4
    5923   135.2    5953   134.5    5993   137.6    6083   139.4    6123     138
    6153   135.1    6173   134.5    6303   136.1    6363   138.6  6623.5   135.4
#Mann= 5 ,-1 , 0
  3543.6     .99       0    4833     .04       0  5063.6     .06       0
    5543      .1       0    5693     .99       0
Levee=0,,,-1,5642.21,134.07,,
Bank Sta=4990.02,5063.6
XS Rating Curve= 0
Exp/Cntr=.3,.1

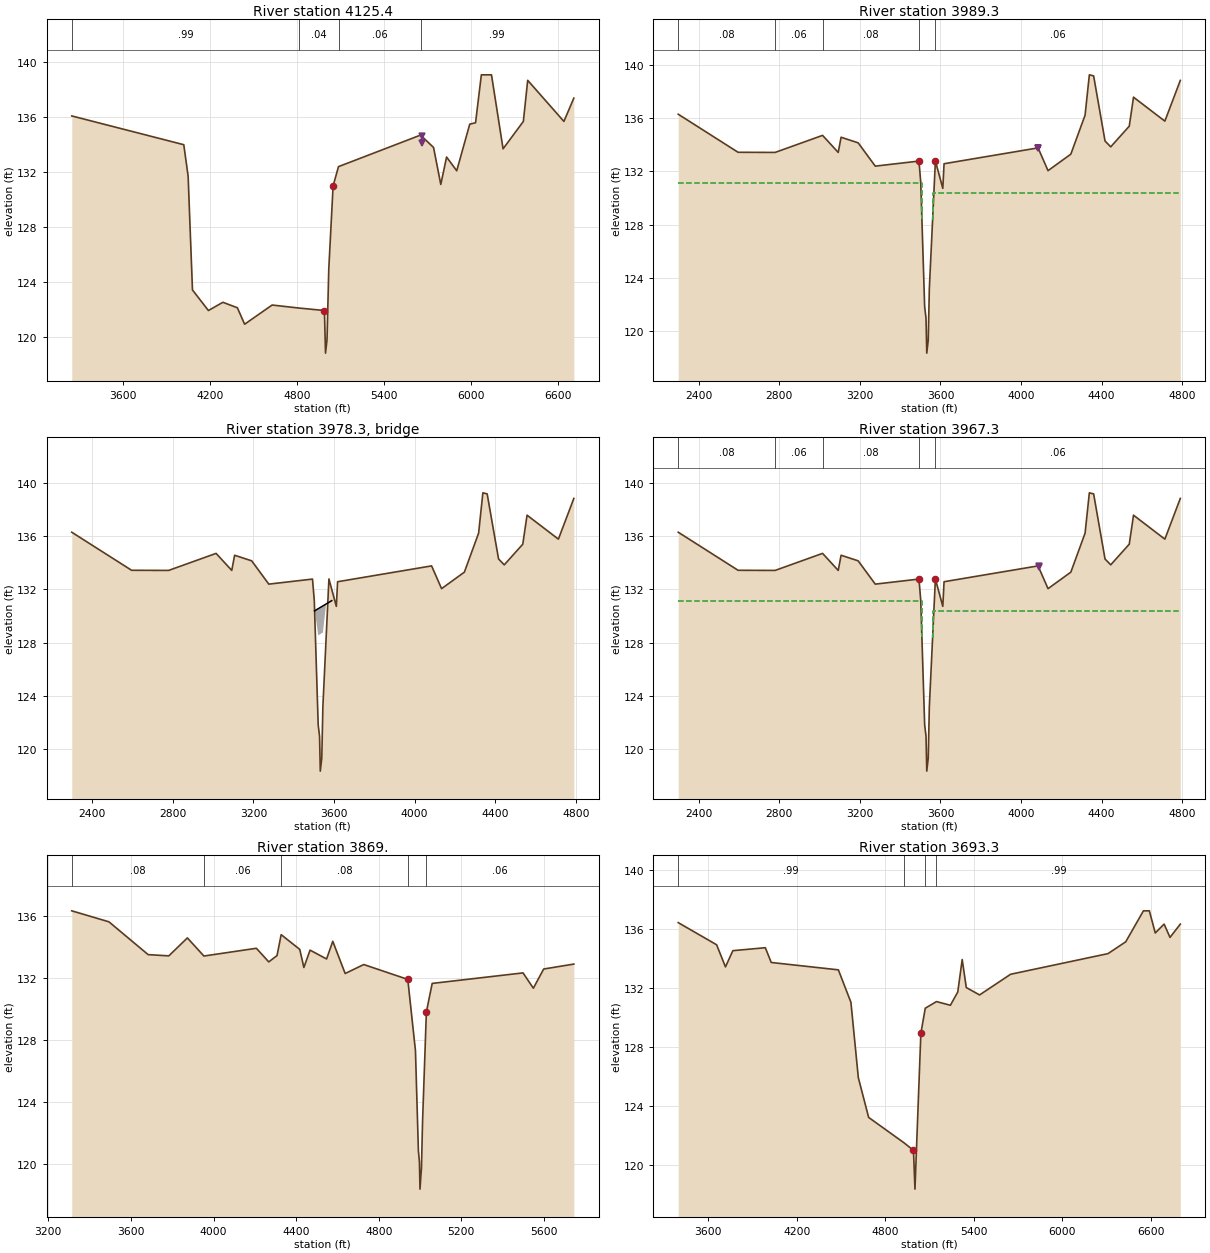
Type RM Length L Ch R = 1 ,4125.4  ,173.4,136.1,94.5
BEGIN DESCRIPTION:
Cross Section K131-04-00_Interpolated- XS5
END DESCRIPTION:
XS GIS Cut Line= 6
      3072828.16     13946127.49      3072083.12     13946334.97
      3071394.67     13946976.27      3071267.35     13946976.27
      3071107.03     13947089.44      3069715.98      13947414.8
#Sta/Elev= 30
  3243.4   136.1  4016.8     134  4046.8   131.7  4076.8   123.4  4186.8   121.9
  4286.8   122.5  4386.8   122.1  4436.8   120.9  4626.8   122.3    4812  122.08
  4987.7   121.9 4995.32  118.79 5005.62  119.76  5017.7   124.9  5047.7     131
    5085   132.4  5651.2   134.7  5741.2   133.8  5791.2   131.1  5831.2   133.1
  5901.2   132.1  5991.2   135.5  6031.2   135.6  6071.2   139.1  6141.2   139.1
  6221.2   133.7  6361.2   135.7  6391.2   138.7  6641.2   135.7  6709.8   137.4
#Mann= 4 ,-1 , 0
  3243.4     .99       0    4812     .04       0    5085     .06       0
  5651.2     .99       0
Levee=0,,,-1,5660.67,134.11,,
Bank Sta=4987.7,5047.7
XS Rating Curve= 0
Exp/Cntr=.5,.3

Type RM Length L Ch R = 1 ,3989.3  ,23.8,22,21.5
BEGIN DESCRIPTION:
Upstream Section of Bridge/Culvert/Weir
END DESCRIPTION:
XS GIS Cut Line= 6
      3072817.92     13946000.32      3071954.37     13946227.85
       3071379.9     13946820.81      3071341.68     13946853.58
      3071156.06      13947015.9      3069695.64      13947393.6
#Sta/Elev= 30
2298.733   136.32595.718  133.442779.566  133.433015.032  134.713092.814  133.43
3106.956  134.573191.809  134.153276.662   132.43493.546  132.783502.385  131.16
 3521.76  121.833528.477  120.983532.224  118.353539.508  119.323545.023  123.21
3575.004  132.793611.845  130.733617.997  132.584084.602  133.77  4134.1  132.06
4247.237   133.34317.947  136.234339.161  139.264360.374  139.184416.942  134.29
4445.227  133.85 4537.15   135.44558.364  137.584713.927  135.784790.578  138.84
#Mann= 5 ,-1 , 0
2298.733     .08       02779.566     .06       03015.032     .08       0
3493.546     .04       03575.004     .06       0
Levee=0,,,-1,4081.91,133.75,,
#XS Ineff= 2 , 0
       03508.105  131.163561.173       0  130.39
Permanent Ineff=
       F       F
Bank Sta=3493.546,3575.004
XS Rating Curve= 0
Skew Angle= 45
Exp/Cntr=.5,.3

Type RM Length L Ch R = 3 ,3978.3  ,,,
BEGIN DESCRIPTION:
PL1_K131-04-00-S4A
END DESCRIPTION:
Bridge Culvert--1,0,-1,-1, 0
Deck Dist Width WeirC Skew NumUp NumDn MinLoCord MaxHiCord MaxSubmerge Is_Ogee
10,2,2.6,45, 2, 2, , , .95, 0, ,,,
  3503.5  3589.2
  130.39  131.16
  128.39  129.16
  3503.5  3589.2
  130.39  131.16
  128.39  129.16
Pier Skew, UpSta & Num, DnSta & Num=  ,3512.24, 2 ,3512.24, 2 , 0 , 0 , 0 ,,
       2       2
     118  123.54
       2       2
     118  123.54
BR Coef= 1 , 1 , 0 ,1.25, 0 ,,,.8,0,2,0,
WSPro=,,,, 1 ,,,, 0 ,,,, 0 ,,,,-1 ,-1 ,-1 , 0 , 0 , 0 , 0 , 0
BC Design=,, 0 ,, 0 ,,,,,,
BC HTab HWMax=139.14

Type RM Length L Ch R = 1 ,3967.3  ,61.4,98.3,141.3
BEGIN DESCRIPTION:
Downstream Section of Bridge/Culvert/Weir
END DESCRIPTION:
XS GIS Cut Line= 6
      3072812.49     13945987.08      3071943.54     13946216.04
      3071365.85     13946812.34      3071328.25     13946844.56
      3071146.12     13947003.83      3069690.29     13947380.34
#Sta/Elev= 30
2298.733   136.32595.718  133.442779.566  133.433015.032  134.713092.814  133.43
3106.956  134.573191.809  134.153276.662   132.43493.546  132.783502.385  131.16
 3521.76  121.833528.477  120.983532.224  118.353539.508  119.323545.023  123.21
3575.004  132.793611.845  130.733617.997  132.584084.602  133.77  4134.1  132.06
4247.237   133.34317.947  136.234339.161  139.264360.374  139.184416.942  134.29
4445.227  133.85 4537.15   135.44558.364  137.584713.927  135.784790.578  138.84
#Mann= 5 ,-1 , 0
2298.733     .08       02779.566     .06       03015.032     .08       0
3493.546     .04       03575.004     .06       0
Levee=0,,,-1,4087.31,133.79,,
#XS Ineff= 2 , 0
       03508.105  131.163561.173       0  130.39
Permanent Ineff=
       F       F
Bank Sta=3493.546,3575.004
XS Rating Curve= 0
Skew Angle= 45
Exp/Cntr=.5,.3

Type RM Length L Ch R = 1 ,3869.   ,177,175.7,171.9
BEGIN DESCRIPTION:
K131-04-00-S4A_PIPELINE -DS - XS 1
END DESCRIPTION:
XS GIS Cut Line= 5
      3072793.02      13945965.8      3071929.63     13946198.74
      3071439.91     13946717.35      3071321.78     13946718.71
      3070618.13     13946777.49
#Sta/Elev= 30
  3313.4  136.33  3493.4  135.62  3683.4   133.5  3783.4  133.42  3873.4  134.58
  3953.4  133.41  4207.6  133.91  4267.6  133.03  4307.6  133.44  4327.6  134.79
  4417.6  133.84  4437.6  132.67  4467.6  133.79  4547.6  133.22  4577.6  134.36
  4637.6  132.28  4727.6  132.86  4940.9   131.9  4978.1  127.29 4992.32  120.83
 4997.25  120.12    5000  118.35 5007.12  119.71  5012.5  122.73  5030.9  129.79
  5059.1  131.64  5499.1  132.32  5549.1  131.33  5599.1  132.57  5745.2  132.89
#Mann= 5 ,-1 , 0
  3313.4     .08       0  3953.4     .06       0  4327.6     .08       0
  4940.9     .04       0  5030.9     .06       0
Bank Sta=4940.9,5030.9
XS Rating Curve= 0
Exp/Cntr=.3,.1

Type RM Length L Ch R = 1 ,3693.3  ,262.2,244,231.1
BEGIN DESCRIPTION:
Cross Section K131-04-00_Interpolated- XS4
END DESCRIPTION:
XS GIS Cut Line= 6
      3072799.86     13945934.16      3071880.36     13946151.07
      3071748.32     13946320.83      3071422.96     13946542.45
      3071045.73     13946561.31      3069668.82     13947075.29
#Sta/Elev= 30
  3397.7   136.4  3657.7   134.9  3717.7   133.4  3767.7   134.5  3987.7   134.7
  4027.7   133.7  4482.4   133.2  4567.5     131  4617.5   125.9  4687.5   123.2
    4927  121.48  4991.2  120.97  5001.2  118.34  5041.2   128.9  5071.1   130.6
    5147  131.05  5241.2   130.8  5291.2   131.7  5321.2   133.9  5348.9     132
  5438.9   131.5  5648.9   132.9  6308.9   134.3  6428.9   135.1  6548.9   137.2
  6588.9   137.2  6628.9   135.7  6688.9   136.3  6728.9   135.4  6798.6   136.3
#Mann= 4 ,-1 , 0
  3397.7     .99       0    4927     .04       0  5071.1     .06       0
    5147     .99       0
Bank Sta=4991.2,5041.2
XS Rating Curve= 0
Exp/Cntr=.3,.1

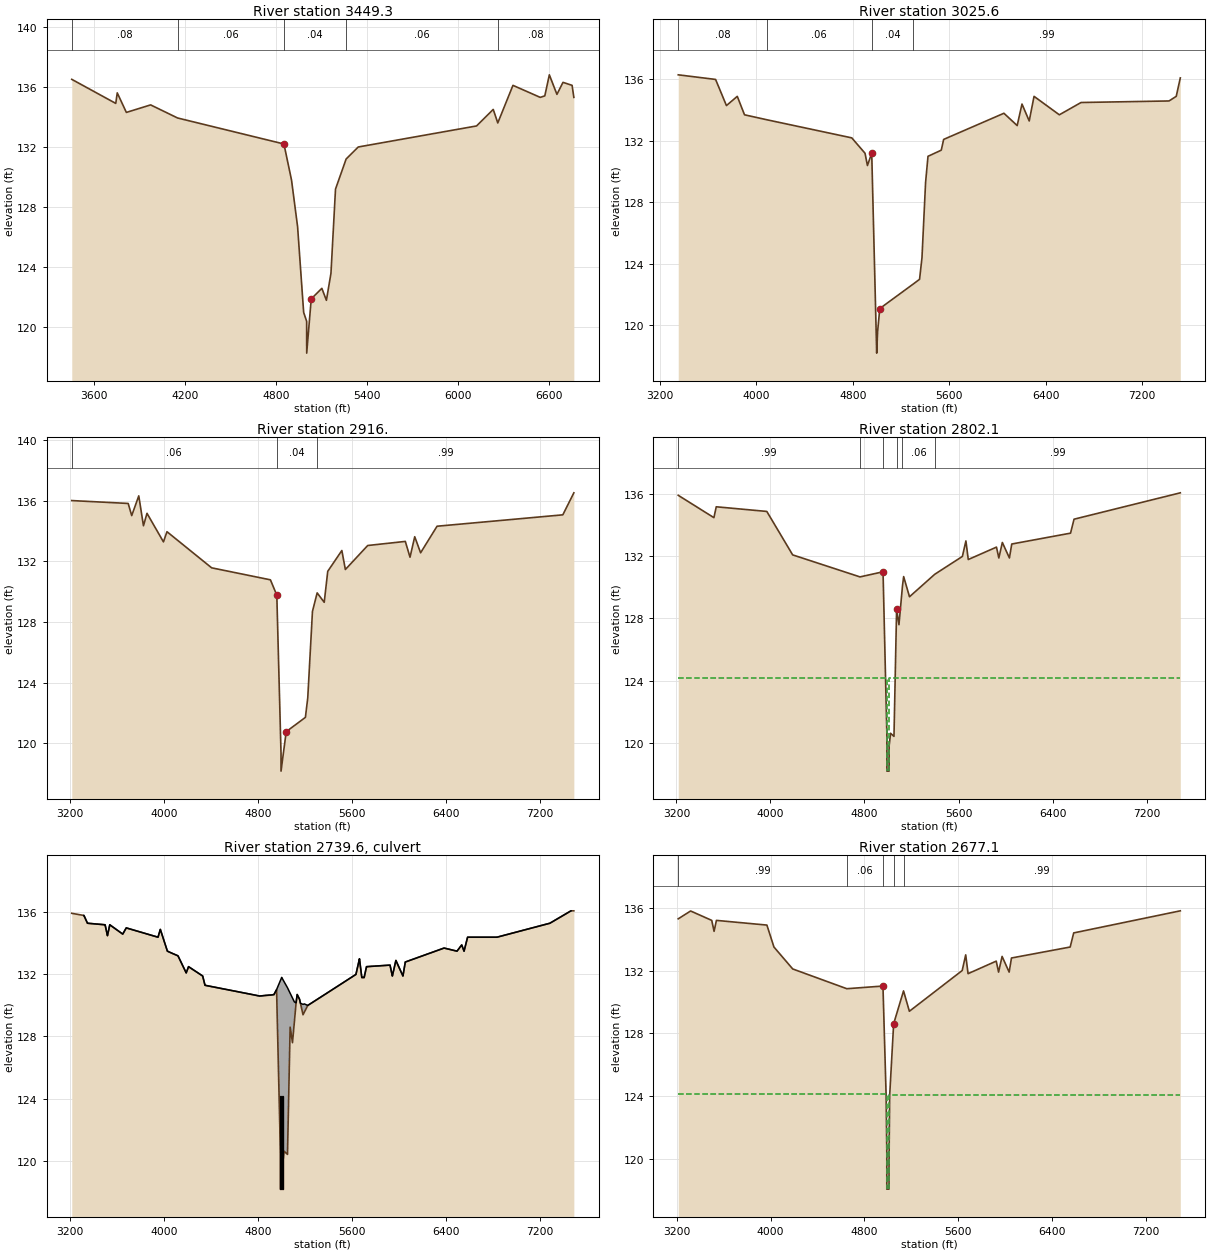
Type RM Length L Ch R = 1 ,3449.3  ,422,423.7,425
BEGIN DESCRIPTION:
Cross Section K131-04-00_Interpolated- XS3
END DESCRIPTION:
XS GIS Cut Line= 3
      3072814.01     13945887.01      3071979.38     13946042.62
      3069701.83     13946976.27
#Sta/Elev= 30
  3452.8   136.5  3742.8   134.9  3752.8   135.6  3812.8   134.3  3972.8   134.8
  4150.3  133.93  4851.7   132.2  4901.8   129.8  4941.8   126.7  4981.8     121
  5001.7   120.4  5001.8  118.29  5031.8   121.9  5101.8   122.6  5131.8   121.8
  5161.8   123.6  5191.8   129.2  5261.8   131.2  5341.7     132  6121.8   133.4
  6231.8   134.5  6261.8   133.6  6361.8   136.1  6541.8   135.3  6571.8   135.4
  6601.8   136.8  6651.8   135.5  6691.8   136.3  6751.8   136.1  6763.3   135.3
#Mann= 5 ,-1 , 0
  3452.8     .08       0  4150.3     .06       0  4851.7     .04       0
  5261.8     .06       0  6261.8     .08       0
Bank Sta=4851.7,5031.8
XS Rating Curve= 0
Exp/Cntr=.3,.1

Type RM Length L Ch R = 1 ,3025.6  ,102.1,109.6,114.1
BEGIN DESCRIPTION:
Cross Section K131-04-00_Interpolated- XS2
END DESCRIPTION:
XS GIS Cut Line= 3
      3072856.45     13945787.98      3071286.21     13945872.86
      3068871.92     13946820.66
#Sta/Elev= 30
  3352.4   136.3  3662.4     136  3752.4   134.3  3842.4   134.9  3902.4   133.7
  4086.2  133.38  4792.4   132.2  4902.4   131.2  4922.4   130.4    4958  131.21
  4999.2   118.2  5006.5  119.58  5024.9   121.1    5300  122.68  5354.9     123
  5374.9   124.4  5404.9   129.3  5424.9     131  5534.9   131.4  5554.9   132.1
  6054.9   133.8  6164.9     133  6204.9   134.4  6264.9   133.3  6304.9   134.9
  6514.9   133.7  6694.9   134.5  7424.9   134.6  7484.9   134.9  7518.6   136.1
#Mann= 4 ,-1 , 0
  3352.4     .08       0  4086.2     .06       0    4958     .04       0
    5300     .99       0
Bank Sta=4958,5024.9
XS Rating Curve= 0
Exp/Cntr=.3,.1

Type RM Length L Ch R = 1 ,2916.   ,103.9,113.9,115
BEGIN DESCRIPTION:
K131-04-00-S3_CULVERT -US - XS 4
END DESCRIPTION:
XS GIS Cut Line= 4
      3072965.15      13945634.4       3071226.8     13945778.97
      3071128.86     13945811.96      3068888.05      13946735.6
#Sta/Elev= 30
  3214.7     136  3694.7  135.81  3724.7  135.01  3784.7  136.31  3824.7  134.34
  3854.7  135.16  3994.7  133.28  4024.7  133.95  4404.7  131.57  4904.7  130.78
  4959.1  129.77 4995.02  119.32 4995.03  118.18  5039.1  120.78  5202.4  121.72
  5222.4  123.01  5262.4   128.7  5302.4  129.92  5362.4   129.3  5392.4  131.34
  5512.4  132.71  5542.4  131.46  5732.4  133.04  6052.4  133.31  6092.4  132.27
  6132.4  133.62  6182.4  132.56  6322.4  134.31  7392.4  135.06  7486.1  136.51
#Mann= 3 ,-1 , 0
  3214.7     .06       0  4959.1     .04       0  5302.4     .99       0
Bank Sta=4959.1,5039.1
XS Rating Curve= 0
Exp/Cntr=.5,.3

Type RM Length L Ch R = 1 ,2802.1  ,126,125,124
BEGIN DESCRIPTION:
Upstream Section of Bridge/Culvert/Weir
END DESCRIPTION:
XS GIS Cut Line= 4
       3072934.4     13945532.71      3071189.23     13945679.59
      3070994.41     13945745.14       3068857.3      13946633.9
#Sta/Elev= 30
  3215.6  135.94  3519.1   134.5  3539.1   135.2  3969.2   134.9  4189.1   132.1
    4762  130.68    4958  131.01 4990.69  120.49  4990.7  118.16 5009.61  118.16
 5009.62  119.77    5022   120.6    5051   120.4  5073.4   128.6  5093.4   127.6
  5123.4   130.1  5133.3   130.7  5183.1   129.4    5398  130.85  5633.1     132
    5663     133    5683   131.8    5923   132.6  5943.1   131.9    5973   132.9
  6033.1   131.9    6053   132.8  6553.1   133.5    6583   134.4    7487   136.1
#Mann= 6 ,-1 , 0
  3215.6     .99       0    4762     .06       0    4958     .04       0
  5073.4     .08       0  5123.4     .06       0    5398     .99       0
#XS Ineff= 2 , 0
       0  4990.7  124.16 5009.61       0  124.16
Permanent Ineff=
       F       F
Bank Sta=4958,5073.4
XS Rating Curve= 0
Exp/Cntr=.5,.3

Type RM Length L Ch R = 2 ,2739.6  ,,,
BEGIN DESCRIPTION:
240'+/- US SPRING-CYPRESS ROAD
Structure ID: K131-04-00-S3
END DESCRIPTION:
Bridge Culvert--1,0,-1,-1, 0
Deck Dist Width WeirC Skew NumUp NumDn MinLoCord MaxHiCord MaxSubmerge Is_Ogee
10,105,2.6,0, 98, 98, , , .95, 0, ,,,
  3319.1  3319.2  3349.1  3349.2  3499.1  3499.2  3519.1  3519.2  3539.1  3539.2
  3649.1  3649.2  3679.1  3679.2  3949.1  3949.2  3969.1  3969.2  4029.1  4029.2
  4069.9  4119.1  4119.2  4189.1  4189.2  4209.1  4209.2  4329.1  4329.2  4349.1
  4349.2  4813.9  4863.8    4914  4929.9  4934.6  4935.6  4947.9    4958  4991.8
  4995.3  4996.4  4999.2  5001.5  5002.2  5004.6  5006.5    5022    5051  5071.4
  5073.4  5093.4  5109.4  5123.4  5133.3  5153.1  5161.3  5183.1  5194.5  5217.4
    5223  5223.1    5633  5633.1    5663  5663.1    5683  5683.1    5703  5703.1
    5723  5723.1    5923  5923.1    5943  5943.1    5973  5973.1    6033  6033.1
    6053  6053.1    6383  6383.1    6493  6493.1    6533  6533.1    6553  6553.1
    6583  6583.1    6833  6833.1    7283  7283.1  7462.8  7462.9
   135.8   135.8   135.3   135.3   135.2   135.2   134.5   134.5   135.2   135.2
   134.6   134.6     135     135   134.4   134.4   134.9   134.9   133.5   133.5
  133.36   133.2   133.2   132.1   132.1   132.5   132.5   131.9   131.9   131.3
   131.3  130.61  130.65  130.68   130.7   130.7   130.7  130.88  131.02  131.63
  131.69  131.71  131.77  131.81   131.8  131.77  131.74  131.53  131.14  130.82
  130.79  130.48  130.23  130.17  130.71  130.41  130.14  130.07   130.1  130.02
     130     130     132     132     133  133.01  131.81   131.8   131.8   131.8
   132.5   132.5   132.6   132.6   131.9   131.9   132.9   132.9   131.9   131.9
   132.8   132.8   133.7   133.7   133.5   133.5   133.9   133.9   133.5   133.5
   134.4   134.4   134.4   134.4   135.3   135.3   136.1   136.1
                                                                                
                                                                                
                                                                                
                                                                                
                                                                                
                                                                                
                                                                                
                                                                                
                                                                                
                                                                
  3319.1  3319.2  3349.1  3349.2  3499.1  3499.2  3519.1  3519.2  3539.1  3539.2
  3649.1  3649.2  3679.1  3679.2  3949.1  3949.2  3969.1  3969.2  4029.1  4029.2
  4069.9  4119.1  4119.2  4189.1  4189.2  4209.1  4209.2  4329.1  4329.2  4349.1
  4349.2  4813.9  4863.8    4914  4929.9  4934.6  4935.6  4947.9    4958  4991.8
  4995.3  4996.4  4999.2  5001.5  5002.2  5004.6  5006.5    5022    5051  5071.4
  5073.4  5093.4  5109.4  5123.4  5133.3  5153.1  5161.3  5183.1  5194.5  5217.4
    5223  5223.1    5633  5633.1    5663  5663.1    5683  5683.1    5703  5703.1
    5723  5723.1    5923  5923.1    5943  5943.1    5973  5973.1    6033  6033.1
    6053  6053.1    6383  6383.1    6493  6493.1    6533  6533.1    6553  6553.1
    6583  6583.1    6833  6833.1    7283  7283.1  7462.8  7462.9
   135.8   135.8   135.3   135.3   135.2   135.2   134.5   134.5   135.2   135.2
   134.6   134.6     135     135   134.4   134.4   134.9   134.9   133.5   133.5
  133.36   133.2   133.2   132.1   132.1   132.5   132.5   131.9   131.9   131.3
   131.3  130.61  130.65  130.68   130.7   130.7   130.7  130.88  131.02  131.63
  131.69  131.71  131.77  131.81   131.8  131.77  131.74  131.53  131.14  130.82
  130.79  130.48  130.23  130.17  130.71  130.41  130.14  130.07   130.1  130.02
     130     130     132     132     133  133.01  131.81   131.8   131.8   131.8
   132.5   132.5   132.6   132.6   131.9   131.9   132.9   132.9   131.9   131.9
   132.8   132.8   133.7   133.7   133.5   133.5   133.9   133.9   133.5   133.5
   134.4   134.4   134.4   134.4   135.3   135.3   136.1   136.1
                                                                                
                                                                                
                                                                                
                                                                                
                                                                                
                                                                                
                                                                                
                                                                                
                                                                                
                                                                
BR Coef= 1 , 0 , 0 ,1.25, 0 ,,,.8,-1,2,0,
WSPro=,,,, 1 ,,,, 0 ,,,, 0 ,,,,-1 ,-1 ,-1 , 0 , 0 , 0 , 0 , 0
Culvert=2,6,8,105,.015,.4,1,8,1,118.16,4994.7,118.1,4994.7,Culvert #1  , 0 ,10
Culvert Bottom n=.015
Culvert=2,6,8,105,.015,.4,1,8,1,118.16,5005.6,118.05,5005.6,Culvert #2  , 0 ,10
Culvert Bottom n=.015
BR U #Sta/Elev= 97
  3215.6  135.94  3319.1   135.8  3319.2   135.8  3349.1   135.3  3349.2   135.3
  3499.1   135.2  3499.2   135.2  3519.1   134.5  3519.2   134.5  3539.1   135.2
  3539.2   135.2  3649.1   134.6  3649.2   134.6  3679.1     135  3679.2     135
  3949.1   134.4  3949.2   134.4  3969.1   134.9  3969.2   134.9  4029.1   133.5
  4029.2   133.5  4069.9  133.36  4119.1   133.2  4119.2   133.2  4189.1   132.1
  4189.2   132.1  4209.1   132.5  4209.2   132.5  4329.1   131.9  4329.2   131.9
  4349.1   131.3  4349.2   131.3    4752   130.7  4813.9   130.6  4863.8  130.64
    4914  130.67  4929.9  130.69  4934.6  130.69  4935.6  130.69  4947.9  130.87
    4958  131.01 4990.69  120.49  4990.7  118.16 5009.61  118.16 5009.62  119.77
    5022   120.6    5051   120.4  5073.4   128.6  5093.4   127.6  5109.4  128.93
  5123.4   130.1  5133.3   130.7  5153.1   130.4  5161.3  130.13  5183.1   129.4
  5194.5  129.57  5217.4  129.91    5223     130  5223.1     130    5388   130.8
    5633     132  5633.1     132    5663     133  5663.1     133    5683   131.8
  5683.1   131.8    5703   131.8  5703.1   131.8    5723   132.5  5723.1   132.5
    5923   132.6  5923.1   132.6    5943   131.9  5943.1   131.9    5973   132.9
  5973.1   132.9    6033   131.9  6033.1   131.9    6053   132.8  6053.1   132.8
    6383   133.7  6383.1   133.7    6493   133.5  6493.1   133.5    6533   133.9
  6533.1   133.9    6553   133.5  6553.1   133.5    6583   134.4  6583.1   134.4
    6833   134.4  6833.1   134.4    7283   135.3  7283.1   135.3  7462.8   136.1
  7462.9   136.1    7487   136.1
BR U #Mann= 6
  3215.6     .99    4752     .06    4958     .02  5073.4     .08  5123.4     .06
    5388     .99
BR D #Sta/Elev= 94
  3213.7  137.51  3319.1   135.8  3319.2   135.8  3349.1   135.3  3349.2   135.3
  3499.1   135.2  3499.2   135.2  3519.1   134.5  3519.2   134.5  3539.1   135.2
  3539.2   135.2  3649.1   134.6  3649.2   134.6  3679.1     135  3679.2     135
  3949.1   134.4  3949.2   134.4  3969.1   134.9  3969.2   134.9  4029.1   133.5
  4029.2   133.5  4069.9  133.36  4119.1   133.2  4119.2   133.2  4189.1   132.1
  4189.2   132.1  4209.1   132.5  4209.2   132.5  4329.1   131.9  4329.2   131.9
  4349.1   131.3  4349.2   131.3    4650  130.84  4813.9   130.6  4863.8  130.64
    4914  130.67  4929.9  130.69  4934.6  130.69  4935.6  130.69  4947.9  130.87
    4958  131.01    4985     124 4990.69  120.38  4990.7  118.05 5009.61  118.05
 5009.62  119.66    5015     124    5049   128.6  5123.4   130.1  5133.3   130.7
  5153.1   130.4  5161.3  130.13  5183.1   129.4  5194.5  129.57  5217.4  129.91
    5223     130  5223.1     130    5633     132  5633.1     132    5663     133
  5663.1     133    5683   131.8  5683.1   131.8    5703   131.8  5703.1   131.8
    5723   132.5  5723.1   132.5    5923   132.6  5923.1   132.6    5943   131.9
  5943.1   131.9    5973   132.9  5973.1   132.9    6033   131.9  6033.1   131.9
    6053   132.8  6053.1   132.8    6383   133.7  6383.1   133.7    6493   133.5
  6493.1   133.5    6533   133.9  6533.1   133.9    6553   133.5  6553.1   133.5
    6583   134.4  6583.1   134.4    6833   134.4  6833.1   134.4    7283   135.3
  7283.1   135.3  7462.8   136.1  7462.9   136.1  7491.4   136.4
BR D #Mann= 5
  3213.7     .99    4650     .06    4958     .02    5049     .06  5133.3     .99
BC Design=,, 0 ,, 0 ,,,,,,
BC HTab HWMax=136.1

Type RM Length L Ch R = 1 ,2677.1  ,50.1,34.1,33
BEGIN DESCRIPTION:
Downstream Section of Bridge/Culvert/Weir
END DESCRIPTION:
XS GIS Cut Line= 4
      3072908.04     13945411.65      3071160.45     13945558.74
      3070962.68     13945625.28      3068824.93     13946514.31
#Sta/Elev= 30
  3213.7   135.3  3319.2   135.8  3499.2   135.2  3519.1   134.5  3539.1   135.2
  3969.2   134.9  4029.1   133.5  4189.1   132.1    4650  130.84    4958  131.01
    4985     124 4990.69  120.38  4990.7  118.05 5009.61  118.05 5009.62  119.66
    5015     124    5049   128.6  5133.3   130.7  5183.1   129.4  5633.1     132
    5663     133    5683   131.8    5923   132.6  5943.1   131.9    5973   132.9
  6033.1   131.9    6053   132.8  6553.1   133.5    6583   134.4  7491.4  135.81
#Mann= 5 ,-1 , 0
  3213.7     .99       0    4650     .06       0    4958     .02       0
    5049     .06       0  5133.3     .99       0
#XS Ineff= 2 , 0
       0  4990.7   124.1 5009.61       0  124.05
Permanent Ineff=
       F       F
Bank Sta=4958,5049
XS Rating Curve= 0
Exp/Cntr=.5,.3