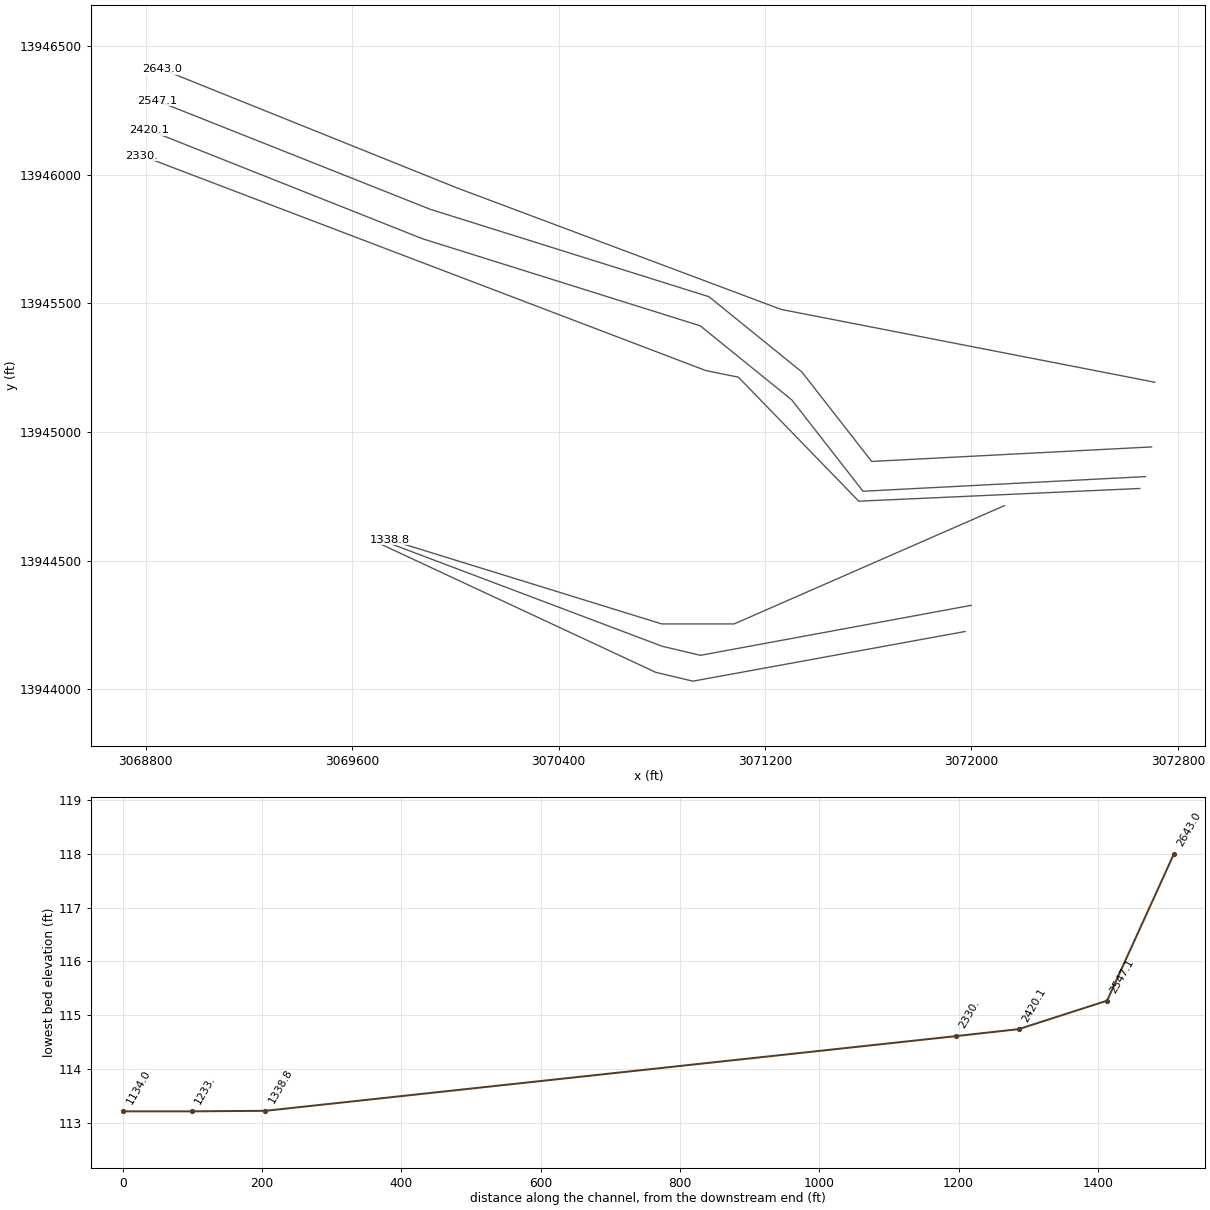
HEC-RAS study K131-04-00.prj: K131-04-00

--- K131-04-00.g01 (geometry) --- (continued)

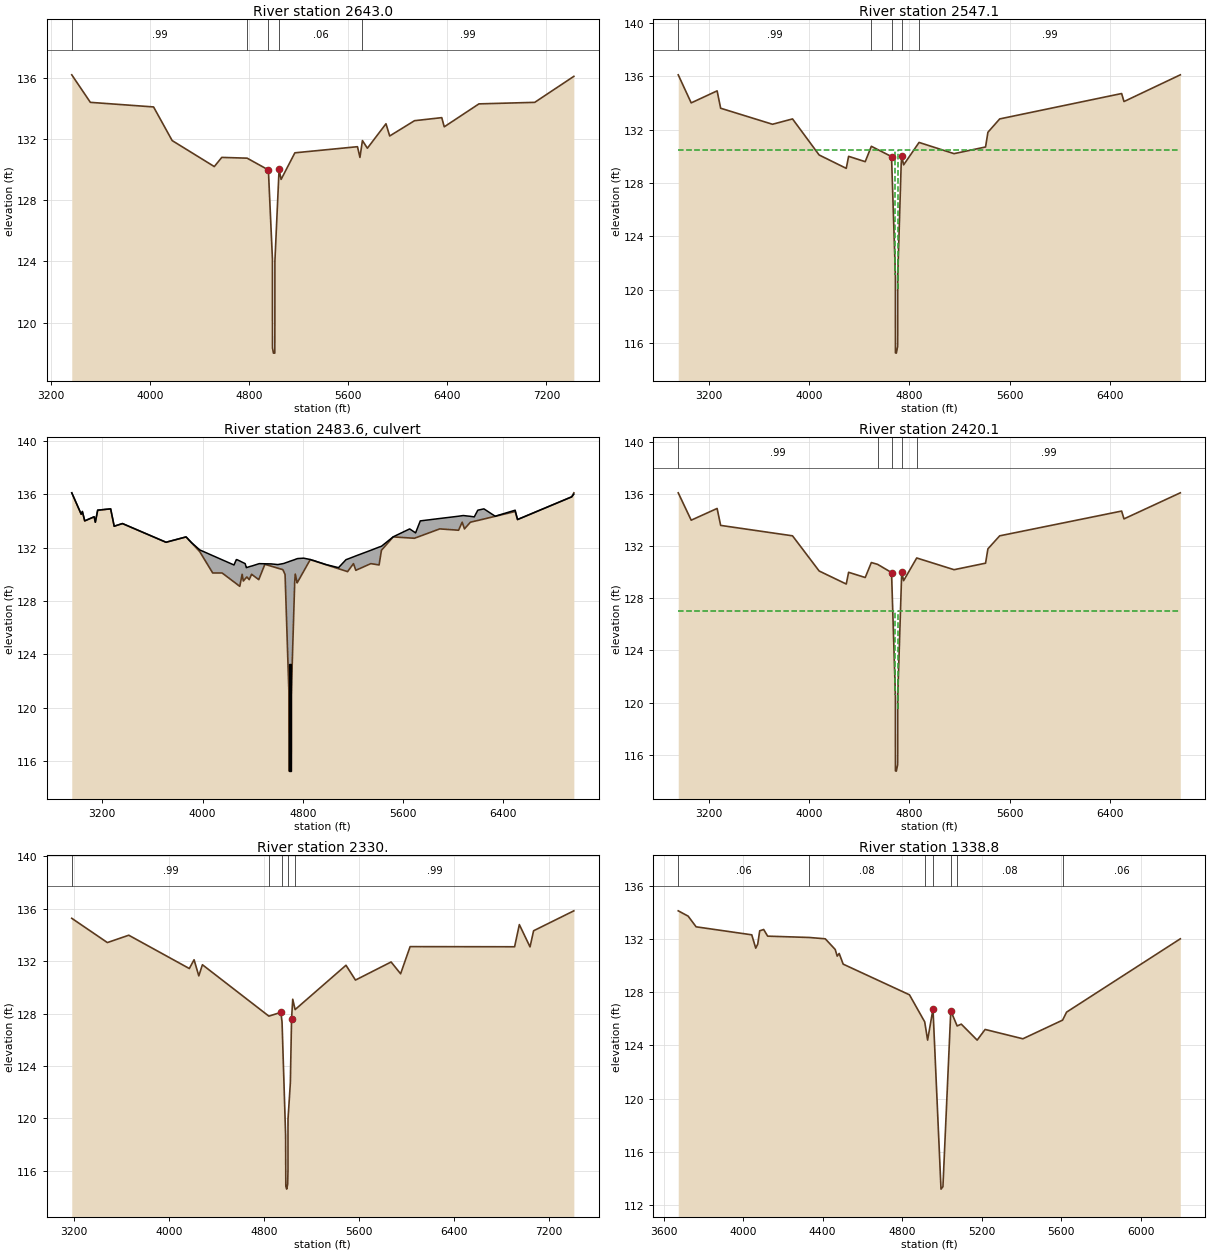
Type RM Length L Ch R = 1 ,2643.0  ,112.2,95.9,81.5
BEGIN DESCRIPTION:
Cross Section K131-04-00_Interpolated- XS1
END DESCRIPTION:
XS GIS Cut Line= 4
      3072710.27     13945193.84      3071262.63     13945476.77
      3070008.33     13945948.31      3068862.48     13946410.42
#Sta/Elev= 30
  3371.1   136.2  3521.1   134.4  4031.1   134.1  4181.1   131.9  4521.1   130.2
  4581.1   130.8    4786  130.75  4957.4  129.98    4990  124.16  4990.3  119.71
  4990.6  118.33  4998.3     118  5009.1     118  5009.7   119.8    5010  124.02
  5043.7  130.02  5059.9  129.36  5171.1   131.1  5676.1   131.5  5696.1   130.8
  5716.1   131.9  5756.1   131.4  5906.1     133  5936.1   132.2  6136.1   133.2
  6356.1   133.4  6376.1   132.8  6656.1   134.3  7106.1   134.4  7421.7   136.1
#Mann= 5 ,-1 , 0
  3371.1     .99       0    4786     .06       0  4957.4     .02       0
  5043.7     .06       0  5716.1     .99       0
#XS Ineff= 2 , 0
       0  4956.7   124.1 5043.61       0  124.05
Permanent Ineff=
       F       F
Bank Sta=4957.4,5043.7
XS Rating Curve= 0
Exp/Cntr=.5,.3

Type RM Length L Ch R = 1 ,2547.1  ,119.2,127,128
BEGIN DESCRIPTION:
Upstream Section of Bridge/Culvert/Weir
END DESCRIPTION:
XS GIS Cut Line= 6
      3072697.87     13944942.44      3071613.33     13944886.03
       3071342.6     13945234.12      3070982.64     13945526.28
      3069902.99     13945865.83      3068845.84     13946286.97
#Sta/Elev= 30
2957.213   136.13060.579     1343267.311   134.93295.502   133.63708.967   132.4
3868.715   132.84081.085   130.14297.214   129.14316.008     1304448.505   129.6
4497.369  130.754658.432  129.984689.066  121.124689.348  116.67 4689.63  115.29
4696.865  115.274707.014  115.774707.578  116.76 4707.86  120.984735.299  129.43
4739.528  130.02 4754.75  129.36 4877.85  131.045156.939   130.25408.213   130.7
5427.006   131.85520.976   132.86493.464   134.76512.258   134.16961.431   136.1
#Mann= 5 ,-1 , 0
2957.213     .99       04497.369     .06       04658.432     .02       0
4739.528     .06       0 4877.85     .99       0
#XS Ineff= 2 , 0
       0 4688.99   130.5  4707.8       0   130.5
Permanent Ineff=
       F       F
Bank Sta=4658.432,4739.528
XS Rating Curve= 0
Skew Angle= 20
Exp/Cntr=.5,.3

Type RM Length L Ch R = 2 ,2483.6  ,,,
BEGIN DESCRIPTION:
SPRING-CYPRESS ROAD
Structure ID: K131-04-00-S1
END DESCRIPTION:
Bridge Culvert--1,0,-1,-1, 0
Deck Dist Width WeirC Skew NumUp NumDn MinLoCord MaxHiCord MaxSubmerge Is_Ogee
10,107,2.6,20, 83, 83, , , .95, 0, ,,,
 2957.21 3032.39 3041.79 3060.58 3135.76 3145.15 3163.95 3267.31  3295.5 3361.28
 3708.97 3868.72  3912.6 3977.72 4081.09 4156.26 4250.89 4269.68 4274.38 4297.21
 4316.01 4325.41 4340.16 4349.56  4353.6 4372.39 4391.18 4392.12 4448.51 4452.26
 4497.37 4547.27 4600.55 4640.58 4650.92 4658.43 4689.07 4689.35 4689.63 4696.87
 4707.01 4707.58 4707.86 4709.65  4735.3 4739.53 4754.75 4758.51 4806.43 4859.25
 4877.85 4887.25 4915.44 4962.42 4981.22 5084.58 5144.63 5156.94 5203.92 5222.72
 5342.43 5408.21 5426.54 5427.01 5520.98 5652.06 5690.12 5699.05 5736.63 5892.06
 6042.41  6070.6 6082.63  6089.4 6136.38  6167.2 6195.39 6244.26  6333.9 6493.47
 6512.26 6944.52 6961.42
   136.1   134.5   134.7     134  134.31   133.9   134.8   134.9   133.6   133.8
   132.4   132.8  132.37  131.83   131.4  131.09   130.7   131.1   131.1     131
  130.91  130.87   130.8   130.5  130.51  130.57  130.62  130.62  130.79   130.8
  130.79  130.78  130.73   130.8  130.82  130.85  130.95  130.95  130.95  130.98
  131.01  131.01  131.01  131.02   131.1  131.12  131.17  131.18  131.21  131.11
  131.05  131.03  130.94   130.8  130.74   130.5   131.1  131.14  131.31  131.38
   131.8  132.04   132.1   132.1  132.81   133.4  133.16   133.1     134  134.18
  134.35  134.39   134.4  134.39  134.34   134.3   134.8   134.9  134.35   134.8
   134.1   135.8     136
                                                                                
                                                                                
                                                                                
                                                                                
                                                                                
                                                                                
                                                                                
                                                                                
                        
 2957.21 3032.39 3041.79 3060.58 3135.76 3145.15 3163.95 3267.31  3295.5 3361.28
 3708.97 3868.72  3912.6 3977.72 4081.09 4156.26 4250.89 4269.68 4274.38 4297.21
 4316.01 4325.41 4340.16 4349.56  4353.6 4372.39 4391.18 4392.12 4448.51 4452.26
 4497.37 4547.27 4600.55 4640.58 4650.92 4658.43 4689.07 4689.35 4689.63 4696.87
 4707.01 4707.58 4707.86 4709.65  4735.3 4739.53 4754.75 4758.51 4806.43 4859.25
 4877.85 4887.25 4915.44 4962.42 4981.22 5084.58 5144.63 5156.94 5203.92 5222.72
 5342.43 5408.21 5426.54 5427.01 5520.98 5652.06 5690.12 5699.05 5736.63 5892.06
 6042.41  6070.6 6082.63  6089.4 6136.38  6167.2 6195.39 6244.26  6333.9 6493.47
 6512.26 6944.52 6961.42
   136.1   134.5   134.7     134   134.1   133.9   134.8   134.9   133.6   133.8
   132.4   132.8  132.37  131.83   131.4  131.09   130.7   131.1   131.1     131
  130.91  130.87   130.8   130.5  130.51  130.57  130.62  130.62  130.79   130.8
  130.79  130.78  130.73   130.8  130.82  130.85  130.95  130.95  130.95  130.98
  131.01  131.01  131.01  131.02   131.1  131.12  131.17  131.18  131.21  131.11
  131.05  131.03  130.94   130.8  130.74   130.5   131.1  131.14  131.31  131.38
   131.8  132.04   132.1   132.1  132.81   133.4  133.16   133.1     134  134.18
  134.35  134.39   134.4  134.39  134.34   134.3   134.8   134.9  134.35   134.8
   134.1   135.8     136
                                                                                
                                                                                
                                                                                
                                                                                
                                                                                
                                                                                
                                                                                
                                                                                
                        
BR Coef= 1 , 0 , 0 ,1.25, 0 ,,,.8,0,2,0,
WSPro=,,,, 1 ,,,, 0 ,,,, 0 ,,,,-1 ,-1 ,-1 , 0 , 0 , 0 , 0 , 0
Culvert=2,8,8,107,.015,.5,1,8,2,115.27,4693,114.75,4693,Culvert #1  , 0 ,10
Culvert Bottom n=.015
Culvert=2,8,8,107,.015,.5,1,8,2,115.29,4703.8,114.76,4703.8,Culvert #2  , 0 ,10
Culvert Bottom n=.015
BR U #Sta/Elev= 83
 2957.21   136.1 3032.39   134.5 3041.79   134.7 3060.58     134 3135.75   134.3
 3145.15   133.9 3163.95   134.8 3267.31   134.9  3295.5   133.6 3361.28   133.8
 3708.97   132.4 3868.72   132.8  3912.6  132.36 3977.72   131.7 4081.09   130.1
 4156.26   130.1 4250.89  129.43 4269.68   129.3 4274.38  129.26 4297.21   129.1
 4316.01     130 4325.41   129.5 4340.16  129.66 4349.56  129.76  4353.6   129.8
 4372.39   129.6 4391.18     130 4392.12     130 4448.51   129.6 4452.26  129.69
 4497.37  130.75 4547.27  130.61 4600.55  130.46 4640.58  130.35 4650.92  130.14
 4658.43  129.98 4689.07  121.12 4689.35  116.67 4689.63  115.29 4696.87  115.27
 4707.01  115.77 4707.58  116.76 4707.86  120.98 4709.65  121.53  4735.3  129.43
 4739.53  130.02 4754.75  129.36 4758.51  129.42 4806.43  130.22 4859.25   131.1
 4877.85  131.04 4887.25  131.02 4915.44  130.93 4962.42  130.79 4981.22  130.73
 5084.58  130.42 5144.63  130.24 5156.94   130.2 5203.92   130.8 5222.72   130.3
 5342.43   130.8 5408.21   130.7 5426.54  131.77 5427.01   131.8 5520.98   132.8
 5652.06  132.72 5690.12   132.7 5699.05  132.73 5736.63  132.86 5892.06   133.4
 6042.41   133.3  6070.6   133.9 6082.63  133.58  6089.4   133.4 6136.38   133.9
  6167.2  133.97 6195.39  134.03 6244.26  134.14  6333.9  134.34 6493.46   134.7
 6512.26   134.1 6944.52   135.8 6961.43   136.1
BR U #Mann= 5
 2957.21     .99 4497.37     .06 4658.43     .02 4739.53     .06 4859.25     .99
BR U Banks=4658.43,4739.53
BR D #Sta/Elev= 83
 2957.21   136.1 3032.39   134.5 3041.79   134.7 3060.58     134 3135.75   134.3
 3145.15   133.9 3163.95   134.8 3267.31   134.9  3295.5   133.6 3361.28   133.8
 3708.97   132.4 3868.72   132.8  3912.6  132.36 3977.72   131.7 4081.09   130.1
 4156.26   130.1 4250.89  129.43 4269.68   129.3 4274.38  129.26 4297.21   129.1
 4316.01     130 4325.41   129.5 4340.16  129.66 4349.56  129.76  4353.6   129.8
 4372.39   129.6 4391.18     130 4392.12     130 4448.51   129.6 4452.26  129.69
 4497.37  130.75 4547.27  130.61 4600.55  130.46 4640.58  130.35 4650.92  130.14
 4658.43  129.98 4689.07  120.59 4689.35  116.14 4689.63  114.76 4696.87  114.74
 4707.01  115.24 4707.58  116.23 4707.86  120.45 4709.65     121  4735.3   128.9
 4739.53  130.02 4754.75  129.36 4758.51  129.42 4806.43  130.22 4859.25   131.1
 4877.85  131.04 4887.25  131.02 4915.44  130.93 4962.42  130.79 4981.22  130.73
 5084.58  130.42 5144.63  130.24 5156.94   130.2 5203.92   130.8 5222.72   130.3
 5342.43   130.8 5408.21   130.7 5426.54  131.77 5427.01   131.8 5520.98   132.8
 5652.06  132.72 5690.12   132.7 5699.05  132.73 5736.63  132.86 5892.06   133.4
 6042.41   133.3  6070.6   133.9 6082.63  133.58  6089.4   133.4 6136.38   133.9
  6167.2  133.97 6195.39  134.03 6244.26  134.14  6333.9  134.34 6493.46   134.7
 6512.26   134.1 6944.52   135.8 6961.43   136.1
BR D #Mann= 5
 2957.21     .99 4547.27     .06 4658.43     .02 4739.53     .06 4859.25     .99
BR D Banks=4658.43,4739.53
BC Design=,, 0 ,, 0 ,,,,,,
BC HTab HWMax=136.1

Type RM Length L Ch R = 1 ,2420.1  ,76.9,90.1,119.8
BEGIN DESCRIPTION:
Downstream Section of Bridge/Culvert/Weir
END DESCRIPTION:
XS GIS Cut Line= 6
      3072674.83     13944827.17      3071579.87     13944770.22
      3071303.89     13945125.06      3070949.03     13945413.14
      3069872.47     13945751.57      3068814.36     13946173.09
#Sta/Elev= 30
 2957.21   136.1 3060.58     134 3267.31   134.9  3295.5   133.6 3868.72   132.8
 4081.09   130.1 4297.21   129.1 4316.01     130 4448.51   129.6 4497.37  130.75
 4547.27  130.61 4658.43  129.98 4689.07  120.59 4689.35  116.14 4689.63  114.76
 4696.87  114.74 4707.01  115.24 4707.58  116.23 4707.86  120.45 4739.52  130.02
 4739.53  130.02 4754.75  129.36 4859.25   131.1 5156.94   130.2 5408.21   130.7
 5427.01   131.8 5520.98   132.8 6493.46   134.7 6512.26   134.1 6961.43   136.1
#Mann= 5 ,-1 , 0
 2957.21     .99       0 4547.27     .06       0 4658.43     .04       0
 4739.53     .06       0 4859.25     .99       0
#XS Ineff= 2 , 0
       0 4688.99     127  4707.8       0     127
Permanent Ineff=
       F       F
Bank Sta=4658.43,4739.52
XS Rating Curve= 0
Skew Angle= 20
Exp/Cntr=.5,.3

Type RM Length L Ch R = 1 ,2330.   ,976.3,991.2,997
BEGIN DESCRIPTION:
K131-04-00-S1_SPRING CYPRESS RD -DS - XS 1
END DESCRIPTION:
XS GIS Cut Line= 5
       3072652.4       13944781.      3071563.32      13944731.5
      3071096.86     13945213.52      3070970.94     13945239.08
      3068785.98     13946073.76
#Sta/Elev= 30
  3179.9  135.26  3479.9  133.41  3659.9  133.97  4169.9  131.43  4209.9   132.1
  4249.9  130.87  4280.2  131.72    4840   127.8  4940.9  128.09  4950.9  127.35
  4980.9  118.72 4982.73  114.83    4990  114.61 4998.43     115 5000.85  116.08
 5001.13  119.96  5020.9  122.71  5030.9  127.58  5040.9  129.09  5060.9   128.3
  5489.4  131.68  5569.4  130.55  5869.4  131.93  5949.4  131.03  6029.4   133.1
  6909.4  133.09  6949.4  134.78  7039.4  133.08  7069.4  134.31  7408.4  135.83
#Mann= 5 ,-1 , 0
  3179.9     .99       0    4840     .06       0  4950.9     .04       0
 4998.43     .06       0  5060.9     .99       0
Bank Sta=4940.9,5030.9
XS Rating Curve= 0
Exp/Cntr=.3,.1

Type RM Length L Ch R = 1 ,1338.8  ,113.8,105.8,98.2
BEGIN DESCRIPTION:
Cross Section K131-04-00-X01
END DESCRIPTION:
XS GIS Cut Line= 4
      3072127.77     13944714.36      3071080.65     13944254.69
      3070799.89     13944254.69      3069747.04     13944581.15
#Sta/Elev= 30
  3673.3   134.1  3723.3   133.7  3763.3   132.9  4043.3   132.3  4063.3   131.3
  4073.3   131.6  4083.3   132.6  4103.3   132.7  4123.3   132.2  4333.3   132.1
  4413.3     132  4463.3   131.2  4473.3   130.7  4483.3   130.9  4503.3   130.1
  4836.9   127.8  4913.6  125.77  4928.3   124.4  4955.3  126.74  4995.7  113.22
  5005.3   113.4  5044.9   126.6  5076.9  125.46  5097.6   125.6  5177.6   124.4
  5217.6   125.2  5407.6   124.5  5607.6   125.9  5627.6   126.5  6199.9     132
#Mann= 7 ,-1 , 0
  3673.3     .06       0  4333.3     .08       0  4913.6     .06       0
  4955.3     .04       0  5044.9     .06       0  5076.9     .08       0
  5607.6     .06       0
Bank Sta=4955.3,5044.9
XS Rating Curve= 0
Exp/Cntr=.3,.1

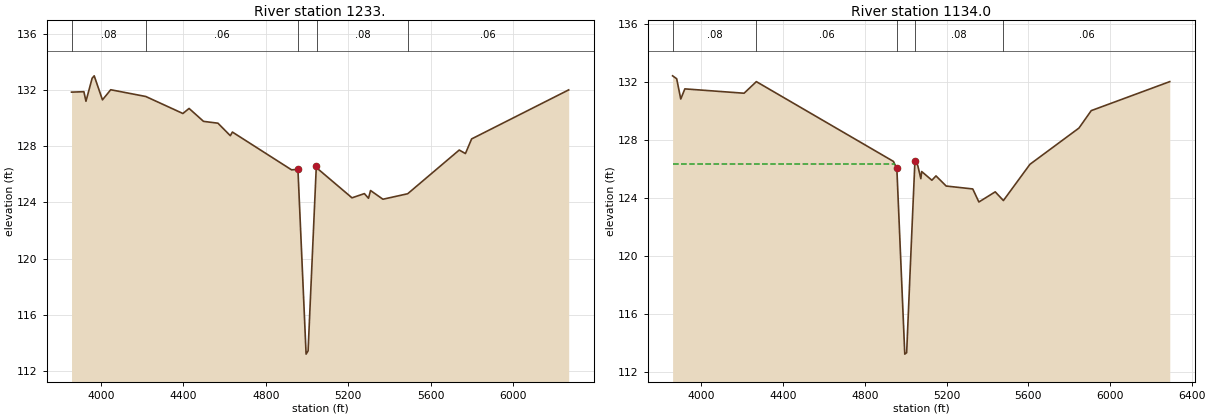
Type RM Length L Ch R = 1 ,1233.   ,104.4,99,98
BEGIN DESCRIPTION:
DAM S2_US FIELD - XS 4
END DESCRIPTION:
XS GIS Cut Line= 4
      3071999.16      13944326.9      3070949.98     13944132.67
      3070801.25     13944167.95      3069687.74     13944589.83
#Sta/Elev= 30
  3858.3  131.85  3918.3  131.88  3928.3   131.2  3958.3  132.84  3968.3  133.01
  4008.3   131.3  4048.3  132.02  4218.3  131.54  4398.3  130.33  4428.3  130.69
  4498.3  129.77  4568.3  129.64  4628.3  128.75  4638.3  129.01  4925.3  126.32
 4956.07  126.36 4995.65  113.21 5005.31  113.44 5045.16  126.57 5049.59  126.43
  5218.2  124.33  5278.2  124.63  5298.2   124.3  5308.2  124.85  5368.2  124.23
  5488.2  124.62  5738.2  127.73  5768.2  127.48  5798.2  128.52  6268.9  132.01
#Mann= 5 ,-1 , 0
  3858.3     .08       0  4218.3     .06       0 4956.07     .04       0
 5049.59     .08       0  5488.2     .06       0
Bank Sta=4956.07,5045.16
XS Rating Curve= 0
Exp/Cntr=.7,.5

Type RM Length L Ch R = 1 ,1134.0  ,9.6,21,22
BEGIN DESCRIPTION:
Upstream Section of Bridge/Culvert/Weir
END DESCRIPTION:
XS GIS Cut Line= 4
      3071975.51     13944225.21      3070920.85     13944032.26
       3070777.6     13944066.25      3069677.48     13944580.54
#Sta/Elev= 26
    3859   132.4    3879   132.2    3899   130.8    3919   131.5    4209   131.2
    4269     132  4939.9   126.5  4956.8  126.01  4995.6  113.21  5004.8  113.31
  5026.7  120.53  5045.4  126.55  5058.7  126.24  5074.3  125.31  5078.4   125.8
  5128.4   125.2  5148.4   125.5  5198.4   124.8  5328.4   124.6  5358.4   123.7
  5438.4   124.4  5478.4   123.8  5608.4   126.3  5848.4   128.8  5908.4     130
  6292.8     132
#Mann= 5 ,-1 , 0
    3859     .08       0    4269     .06       0  4956.8     .04       0
  5045.4     .08       0  5478.4     .06       0
#XS Ineff= 2 , 0
       0  4946.8  126.31  5055.4       0   123.7
Permanent Ineff=
       F       F
Bank Sta=4956.8,5045.4
XS Rating Curve= 0
Exp/Cntr=.7,.5