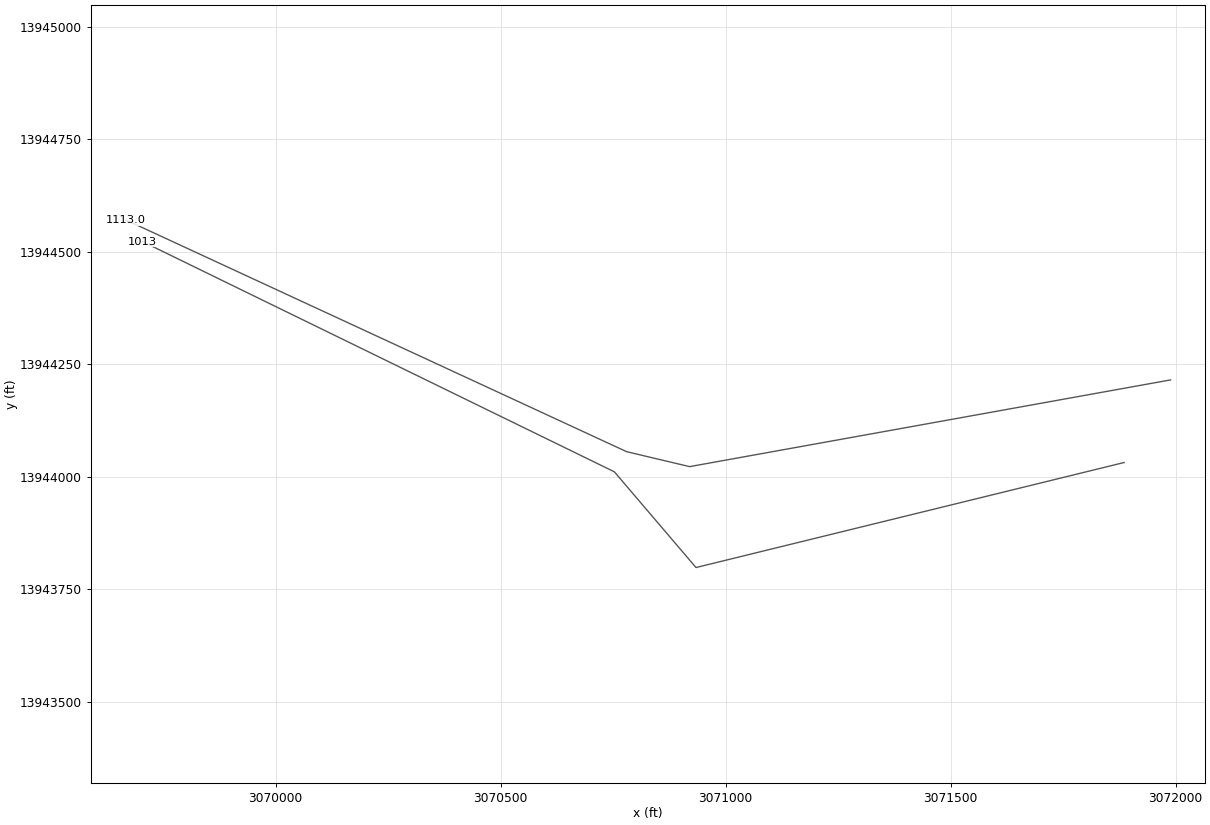
HEC-RAS study K131-04-00.prj: K131-04-00

--- K131-04-00.g01 (geometry) --- (continued)

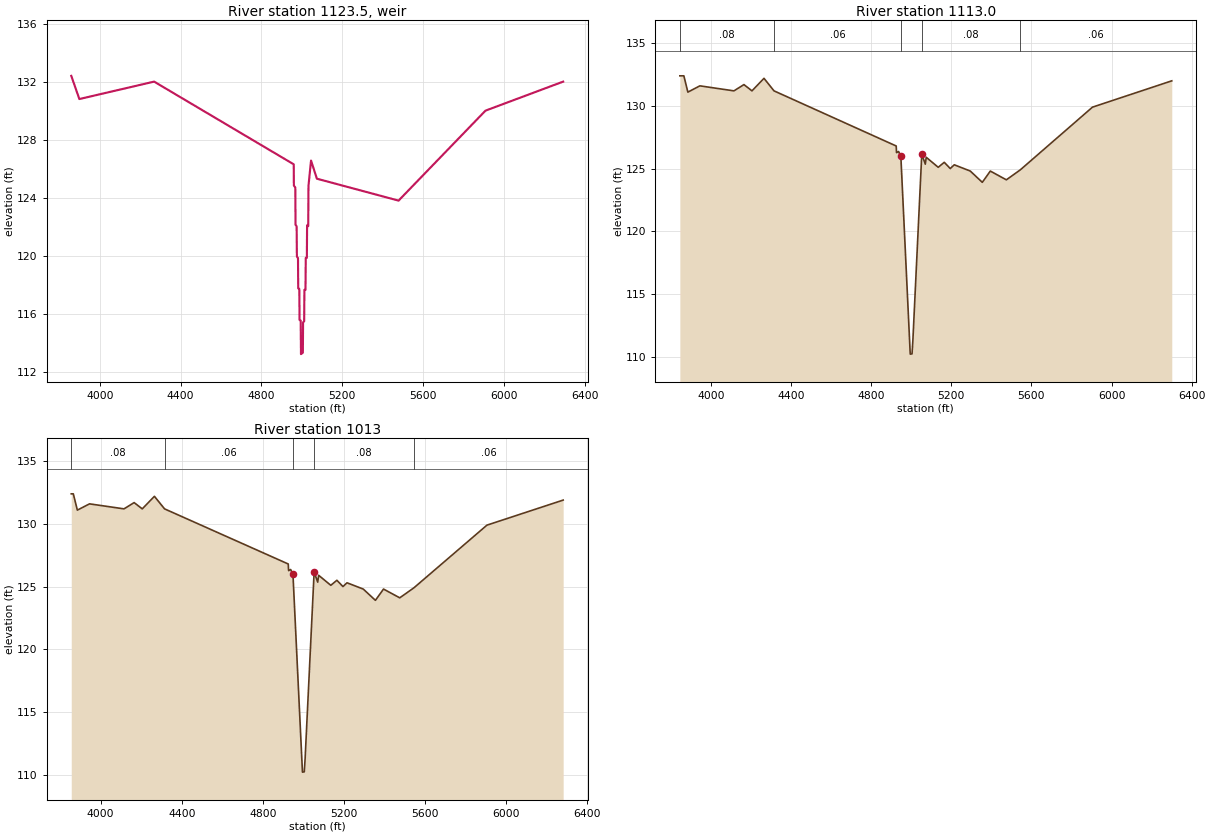
Type RM Length L Ch R = 5 ,1123.5  ,,,
BEGIN DESCRIPTION:
SHEET PILE WEIR 1350' D/S SPRING CYPRESS
Structure ID: K131-04-00-S2
END DESCRIPTION:
IW Pilot Flow=0
#Inline Weir SE= 30
    3859   132.4    3899   130.8    4269     132  4959.8   126.3  4960.4  124.84
  4967.5   124.7  4968.6  122.14  4974.1  122.02  4975.3  119.94  4980.8  119.84
  4981.9  117.75  4987.3  117.71  4988.5  115.58  4994.1  115.53  4995.6  113.22
  5004.8  113.32  5005.9  115.41  5011.3  115.48  5012.5  117.65  5017.9  117.65
  5019.2  119.85  5024.6  119.85  5025.8   122.1  5031.4  122.04  5032.6  124.82
  5045.4  126.56  5074.3  125.31  5478.4   123.8  5908.4     130  6292.8     132
IW Dist,WD,Coef,Skew,MaxSub,Min_El,Is_Ogee,SpillHt,DesHd
10,1,3,0,.95,, 0 ,,,0,0,

Type RM Length L Ch R = 1 ,1113.0  ,125,100,75
BEGIN DESCRIPTION:
Cross Section FIELD_DS
Located At: SHEET PILE WEIR 1350' D/S SPRING CYPRESS
END DESCRIPTION:
XS GIS Cut Line= 4
      3071988.79     13944215.25      3070920.04     13944022.55
      3070780.03     13944055.73      3069667.52     13944570.58
#Sta/Elev= 30
    3845   132.4    3865   132.4    3885   131.1    3945   131.6    4115   131.2
    4165   131.7    4205   131.2    4265   132.2    4315   131.2    4925   126.8
  4926.7  126.27  4936.9  126.36  4948.3  125.97  4995.1  110.19    5004  110.21
  5008.3  111.29  5052.7  126.16  5070.4  125.35  5074.9   125.9  5134.9   125.1
  5164.9   125.5  5194.9     125  5214.9   125.3  5294.9   124.8  5354.9   123.9
  5394.9   124.8  5474.9   124.1  5544.9   124.9  5904.9   129.9  6300.7     132
#Mann= 5 ,-1 , 0
    3845     .08       0    4315     .06       0  4948.3     .04       0
  5052.7     .08       0  5544.9     .06       0
Bank Sta=4948.3,5052.7
XS Rating Curve= 0
Exp/Cntr=.7,.5

Type RM Length L Ch R = 1 ,1013    ,0,0,0
BEGIN DESCRIPTION:
Cross Section FIELD_DS- XS 1
Located At: SHEET PILE WEIR 1350' D/S SPRING CYPRESS
END DESCRIPTION:
XS GIS Cut Line= 4
      3071885.61      13944031.7      3070934.17      13943798.3
      3070752.75       13944011.      3069704.15      13944522.7
#Sta/Elev= 30
  3854.9   132.4    3865   132.4    3885   131.1    3945   131.6    4115   131.2
    4165   131.7    4205   131.2    4265   132.2    4315   131.2    4925   126.8
  4926.7  126.27  4936.9  126.36  4948.3  125.97  4995.1  110.19    5004  110.21
  5008.3  111.29  5052.7  126.16  5070.4  125.35  5074.9   125.9  5134.9   125.1
  5164.9   125.5  5194.9     125  5214.9   125.3  5294.9   124.8  5354.9   123.9
  5394.9   124.8  5474.9   124.1  5544.9   124.9  5904.9   129.9  6280.9   131.9
#Mann= 5 ,-1 , 0
  3854.9     .08       0    4315     .06       0  4948.3     .04       0
  5052.7     .08       0  5544.9     .06       0
Bank Sta=4948.3,5052.7
XS Rating Curve= 0
Exp/Cntr=.3,.1

Chan Stop Cuts=-1